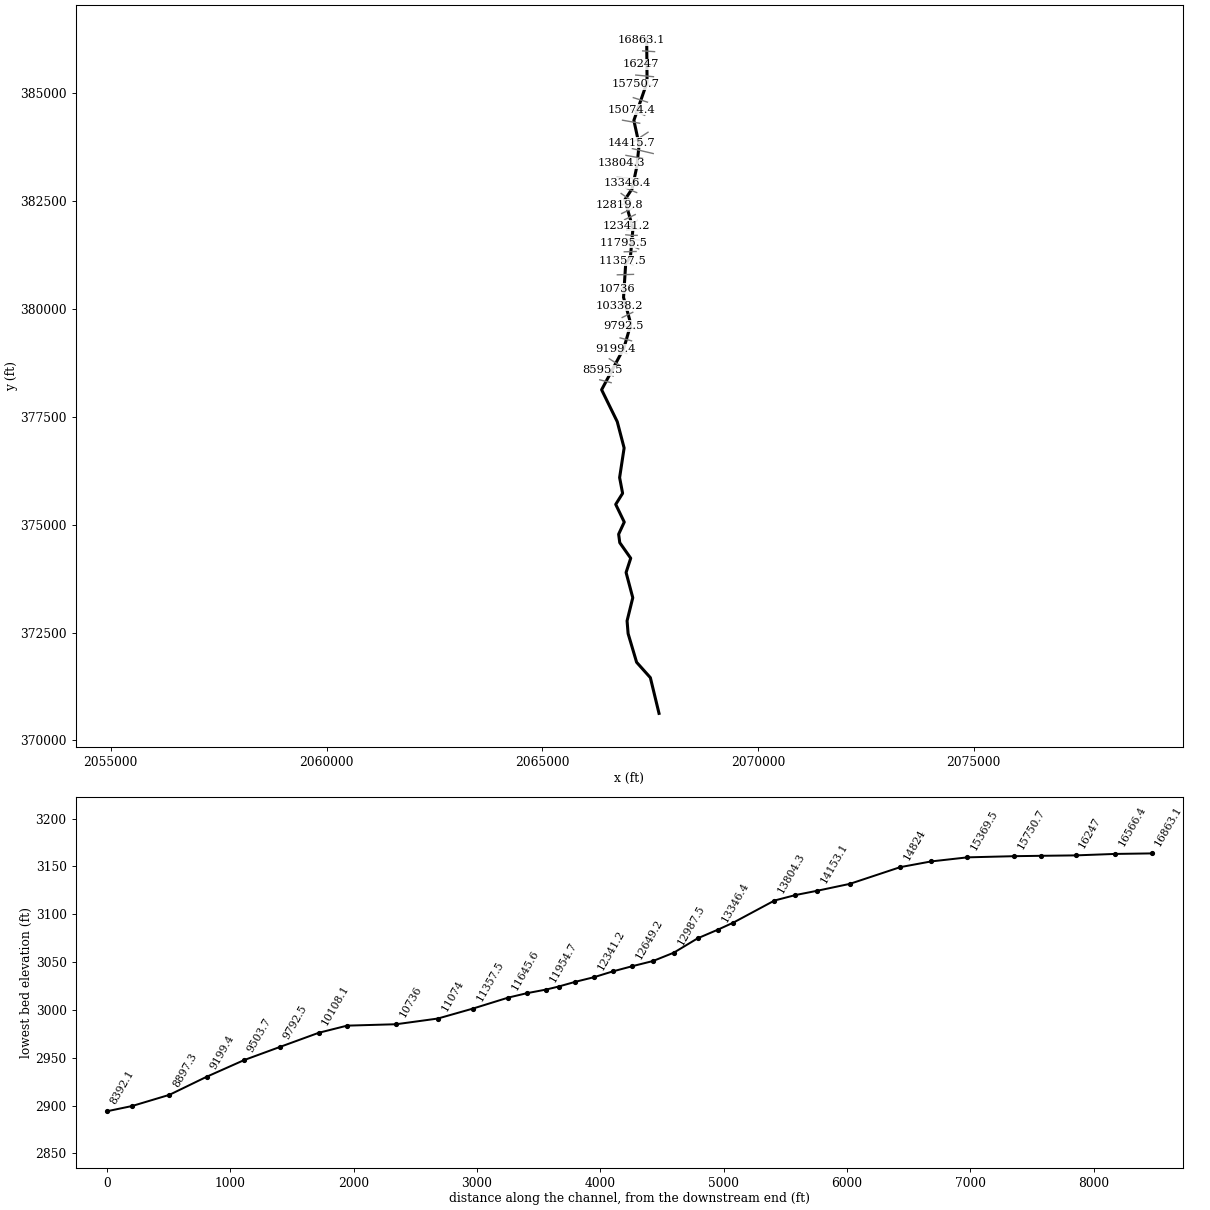
--- BrownCreek.prj (project) ---

Proj Title=BrownCreek
Current Plan=p01
Default Exp/Contr=0,0
English Units
Geom File=g01
Flow File=f01
Plan File=p01
BEGIN DESCRIPTION:
END DESCRIPTION:
DSS Export Rating Curves= 0
DSS Export Rating Curve Sorted= 0
DSS Export Volume Flow Curves= 0
DXF OffsetX= 0
DXF OffsetY= 0
DXF ScaleX= 0
DXF ScaleY= 0

--- BrownCreek.p01 (plan) ---

Plan Title=Floodplain
Program Version=4.00
Geom File=g01
Flow File=f01
K Sum by GR=0
Std Step Tol=0.01
Critical Tol=0.01
Num of Std Step Trials=20
Max Error Tol=0.3
Flow Tol Ratio=0.001
Split Flow NTrial=30
Split Flow Tol=0.02
Split Flow Ratio=0.02
Log Output Level=0
Friction Slope Method=1
Unsteady Friction Slope Method=2
Unsteady Bridges Friction Slope Method=1
Global Log Level=0
CheckData=False
Run HTab=0
Run UNet=0
Run PostProcess=0
UNET Theta=0
UNET Theta Warmup=0
UNET ZTol=0
UNET ZSATol=0
UNET MxIter=0
UNET MaxInSteps=0
UNET DtIC=0
UNET DtMin=0
UNET MaxCRTS=0
UNET WFStab=0
UNET SFStab=0
UNET WFX=0
UNET SFX=0
UNET DSS MLevel=0
UNET DZMax Abort=0
UNET Convert EG Bridges=0
UNET Use Existing IB Tables=0
UNET Froude Limit=0
UNET Froude Power=0
Write IC File=0
Echo Input=False
Echo Output=False
Write Detailed=0

--- BrownCreek.f01 (steady flow) ---

Flow Title=NFF Regression Equation
Program Version=4.00
Number of Profiles=1
Profile Names=P100yr
River Rch & RM=BrownCreek,Main      ,16863.1
635.9109
River Rch & RM=BrownCreek,Main      ,14415.7
678.7682
River Rch & RM=BrownCreek,Main      ,14153.1
796.1442
River Rch & RM=BrownCreek,Main      ,12649.2
871.4078
River Rch & RM=BrownCreek,Main      ,11074
957.5103
River Rch & RM=BrownCreek,Main      ,8595.5
1026.061
River Rch & RM=BrownCreek,Main      ,7673.6
1139.557
River Rch & RM=BrownCreek,Main      ,5826
1208.645
River Rch & RM=BrownCreek,Main      ,3928.4
1308.016
River Rch & RM=BrownCreek,Main      ,230.8
1413.581
Boundary for River Rch & Prof#=BrownCreek,Main      ,1
Up Type=0
Dn Type=3
Dn Slope=0.028361

--- BrownCreek.g01 (geometry) ---

Geom Title=USGS 10m DEM
Program Version=4.00

River Reach=BrownCreek      ,Main
Reach XY= 30
     2067420.136      386261.995     2067429.078      385253.316
       2067123.1      384368.388     2067244.815      383807.377
     2067192.732      383303.905     2067083.357      382786.544
     2066913.218      382527.863     2067101.962      381864.019
     2067044.169      381217.715     2066933.482      381046.037
     2066883.605      380267.154     2067053.205      379647.759
     2066890.562      379089.803     2066375.526       378126.37
     2066737.695      377387.447     2066897.189       376777.81
     2066792.672      376091.343     2066862.143      375726.313
     2066702.394      375469.816     2066900.311      375060.093
     2066770.103      374778.843     2066796.144      374582.663
     2067049.929      374222.237     2066942.623      373891.376
     2067097.794      373307.055     2066965.493      372770.106
     2066989.679      372474.716     2067186.687      371810.926
     2067505.224      371454.389     2067705.854      370626.592

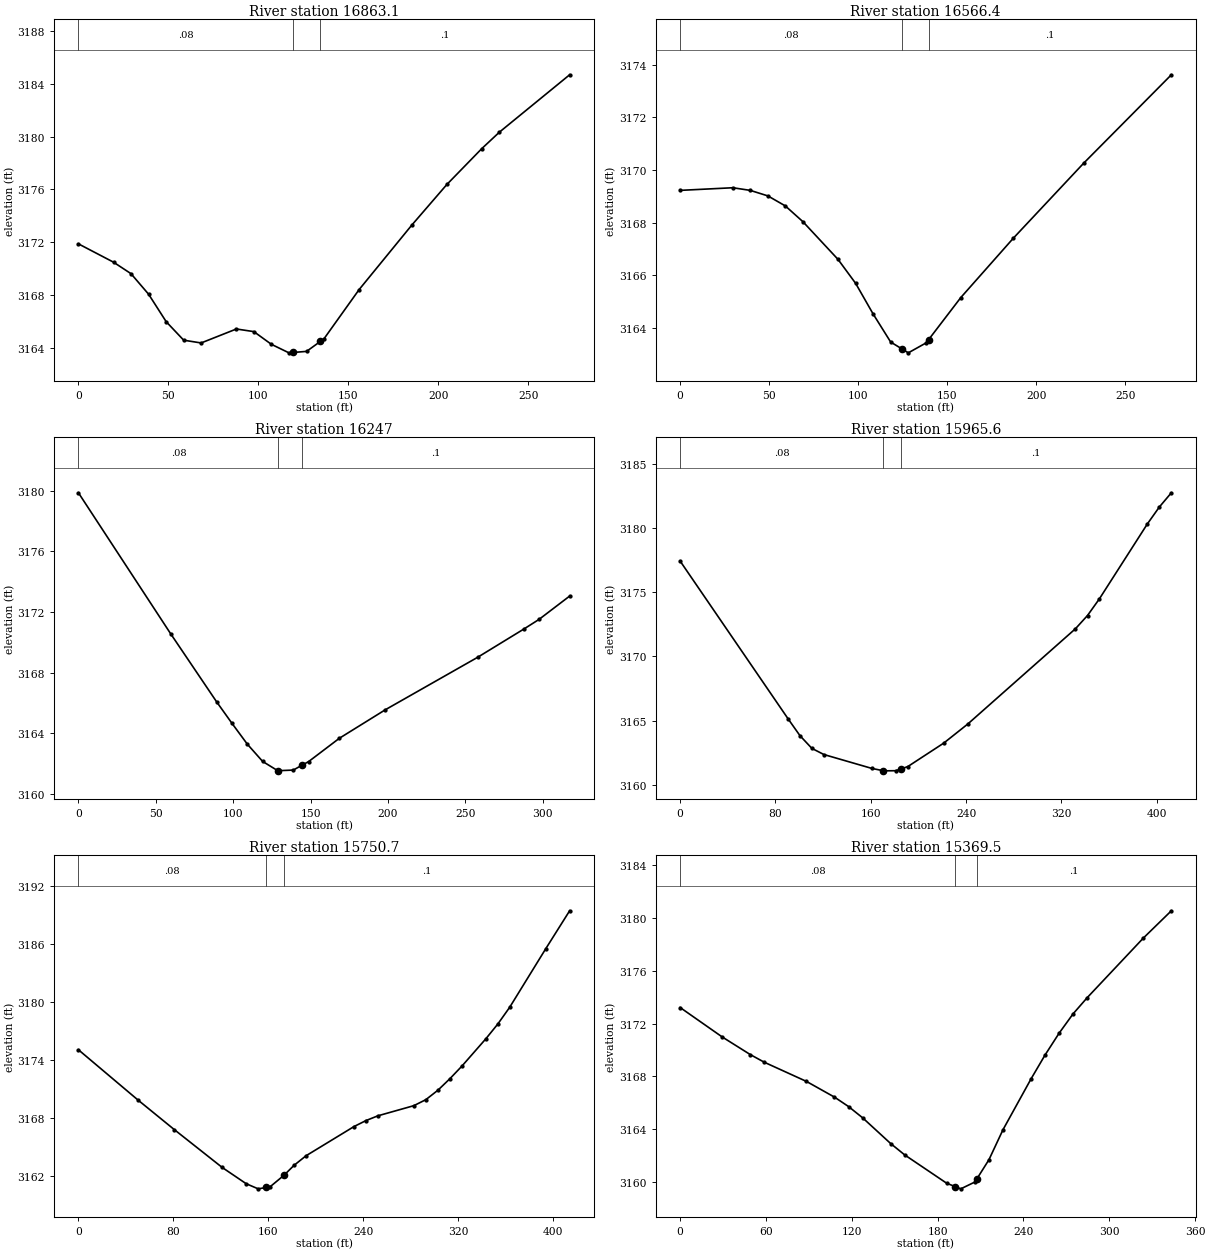
Type RM Length L Ch R = 1 ,16863.1 ,300.4,296.7,293.5
XS GIS Cut Line= 2
     2067558.186      386270.895     2067287.704        386233.9
#Sta/Elev= 21
       0 3171.87    19.5 3170.48    29.2 3169.61      39 3168.05    48.8 3165.96
    58.5 3164.56    68.2 3164.35    87.8 3165.41    97.5 3165.21   107.2 3164.25
     117  3163.6   119.5 3163.63   126.8 3163.71   134.5 3164.47   136.5 3164.67
     156  3168.4   185.2 3173.28   204.8 3176.38   224.2  3179.1     234 3180.35
     273  3184.7
#Mann= 3 , 0 , 0
       0     .08       0   119.5    .045       0   134.5      .1       0
Bank Sta=119.5,134.5
XS Rating Curve= 0 ,0
Exp/Cntr=0.3,0.1

Type RM Length L Ch R = 1 ,16566.4 ,317.6,319.4,319.1
XS GIS Cut Line= 2
      2067602.44      385962.508     2067326.967      385979.698
#Sta/Elev= 18
       0 3169.23    29.6 3169.33    39.4 3169.23    49.3 3169.02    59.1 3168.64
      69 3168.04    88.7 3166.61    98.6  3165.7   108.4 3164.54   118.3 3163.47
   124.6 3163.21   128.2 3163.06     138 3163.43   139.6 3163.56   157.7 3165.16
   187.3 3167.42   226.7 3170.26     276 3173.62
#Mann= 3 , 0 , 0
       0     .08       0   124.6    .045       0   139.6      .1       0
Bank Sta=124.6,139.6
XS Rating Curve= 0 ,0
Exp/Cntr=0.3,0.1

Type RM Length L Ch R = 1 ,16247   ,283,281.4,279.8
XS GIS Cut Line= 2
     2067590.151      385662.046     2067272.912      385668.865
#Sta/Elev= 17
       0 3179.86    59.5 3170.58    89.2 3166.09    99.2 3164.66   109.1 3163.29
     119 3162.15   128.9 3161.53   129.2 3161.54   138.8 3161.58   144.2 3161.89
   148.7 3162.14   168.6 3163.68   198.3 3165.56   257.8 3169.01   287.6 3170.87
   297.5 3171.51   317.3 3173.05
#Mann= 3 , 0 , 0
       0     .08       0   129.2    .045       0   144.2      .1       0
Bank Sta=129.2,144.2
XS Rating Curve= 0 ,0
Exp/Cntr=0.3,0.1

Type RM Length L Ch R = 1 ,15965.6 ,213.8,214.9,216.4
XS GIS Cut Line= 2
     2067577.222      385381.461     2067166.645      385420.104
#Sta/Elev= 19
       0 3177.43    90.5 3165.16   100.6 3163.83   110.6 3162.84   120.7 3162.36
   160.9 3161.28   170.5  3161.1     171 3161.09     181  3161.1   185.5 3161.24
   191.1 3161.42   221.3 3163.25   241.4 3164.73   331.9 3172.16     342 3173.19
     352 3174.49   392.3 3180.33   402.3 3181.64   412.4 3182.75
#Mann= 3 , 0 , 0
       0     .08       0   170.5    .045       0   185.5      .1       0
Bank Sta=170.5,185.5
XS Rating Curve= 0 ,0
Exp/Cntr=0.3,0.1

Type RM Length L Ch R = 1 ,15750.7 ,387.2,381.1,374.7
XS GIS Cut Line= 2
      2067569.64      385182.976     2067156.739       385208.48
#Sta/Elev= 24
       0 3175.09    50.4 3169.87    80.7 3166.84   121.1 3162.92   141.3 3161.24
   151.4 3160.71   158.1 3160.85   161.4 3160.92   173.1 3162.11   181.6 3163.14
   191.7 3164.13   232.1 3167.15   242.2 3167.77   252.2 3168.26   282.5 3169.31
   292.6 3169.93   302.7  3170.9   312.8 3172.09   322.9 3173.39   343.1 3176.22
   353.2 3177.75   363.2 3179.48   393.5 3185.52   413.7 3189.46
#Mann= 3 , 0 , 0
       0     .08       0   158.1    .045       0   173.1      .1       0
Bank Sta=158.1,173.1
XS Rating Curve= 0 ,0
Exp/Cntr=0.3,0.1

Type RM Length L Ch R = 1 ,15369.5 ,297.3,295.2,293
XS GIS Cut Line= 2
      2067438.05      384792.334     2067110.704      384896.204
#Sta/Elev= 24
       0 3173.22    29.4 3170.99    49.1 3169.65    58.9 3169.07    88.3 3167.62
   107.9 3166.43   117.8 3165.71   127.6 3164.86   147.2 3162.91     157 3162.05
   186.4  3159.9   192.3 3159.65   196.2 3159.48   206.1    3160   207.3 3160.21
   215.9 3161.69   225.7 3163.96   245.3 3167.81   255.1 3169.62   264.9 3171.27
   274.7 3172.74   284.6 3173.97   323.8 3178.48   343.4 3180.55
#Mann= 3 , 0 , 0
       0     .08       0   192.3    .045       0   207.3      .1       0
Bank Sta=192.3,207.3
XS Rating Curve= 0 ,0
Exp/Cntr=0.3,0.1

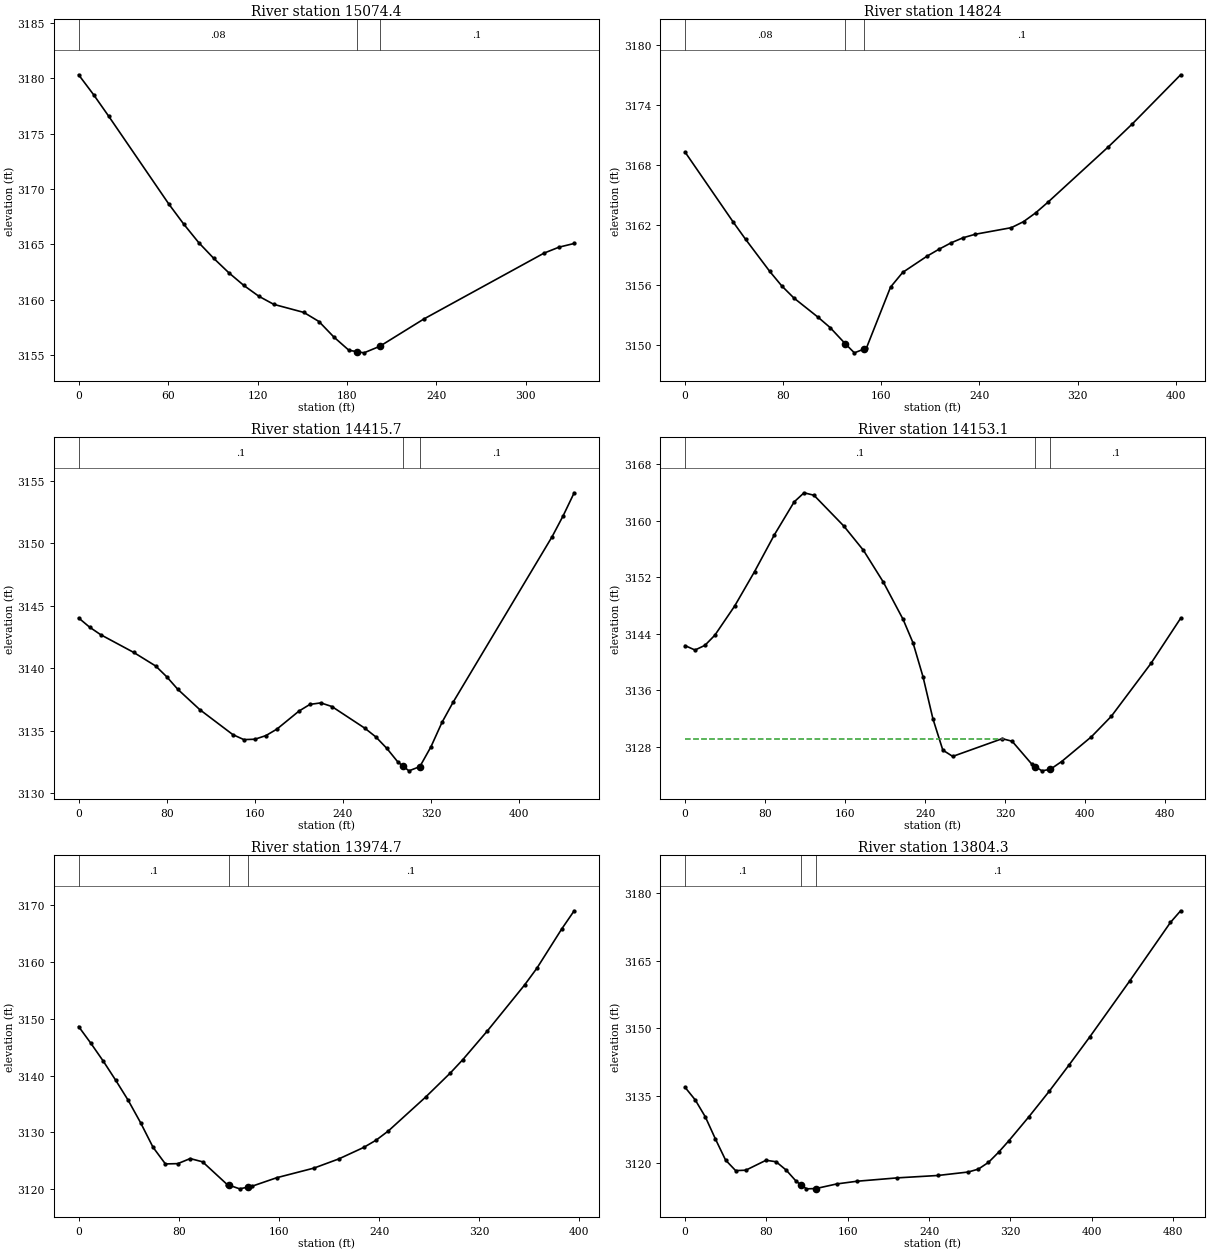
Type RM Length L Ch R = 1 ,15074.4 ,249.8,250.4,256.7
XS GIS Cut Line= 2
     2067373.133      384487.226     2067067.711      384618.323
#Sta/Elev= 22
       0 3180.33    10.1 3178.52    20.1  3176.6    60.4 3168.67    70.5 3166.84
    80.6 3165.16    90.6 3163.75   100.7 3162.45   110.8  3161.3   120.9 3160.32
   130.9 3159.59   151.1 3158.86   161.2 3158.04   171.2 3156.64   181.3 3155.44
     187 3155.31   191.4 3155.21     202  3155.8   231.6 3158.27   312.2 3164.22
   322.3 3164.76   332.4 3165.09
#Mann= 3 , 0 , 0
       0     .08       0     187    .045       0     202      .1       0
Bank Sta=187,202
XS Rating Curve= 0 ,0
Exp/Cntr=0.3,0.1

Type RM Length L Ch R = 1 ,14824   ,391.3,408.3,425.4
XS GIS Cut Line= 2
     2067258.092      384303.181     2066860.291      384373.621
#Sta/Elev= 26
       0  3169.3    39.4 3162.28    49.3 3160.59      69 3157.38    78.8 3155.93
    88.7 3154.72   108.4  3152.8   118.2 3151.77   130.5 3150.16     138 3149.24
   145.5  3149.6   147.8 3149.71   167.5 3155.81   177.4 3157.28   197.1 3158.89
   206.9 3159.59   216.8 3160.23   226.6 3160.74   236.5 3161.09     266 3161.75
   275.9 3162.35   285.8 3163.23   295.6 3164.27   344.9 3169.81   364.6 3172.12
     404 3177.03
#Mann= 3 , 0 , 0
       0     .08       0   130.5    .045       0   145.5      .1       0
Bank Sta=130.5,145.5
XS Rating Curve= 0 ,0
Exp/Cntr=0.3,0.1

Type RM Length L Ch R = 1 ,14415.7 ,278.6,262.5,261.2
XS GIS Cut Line= 2
      2067450.88      384094.629     2067073.814      383849.239
#Sta/Elev= 30
       0 3144.02      10 3143.28      20 3142.68      50 3141.26      70 3140.17
      80 3139.31      90 3138.31     110 3136.68     140 3134.68     150 3134.28
     160 3134.31     170  3134.6     180 3135.12     200 3136.56     210  3137.1
   219.9 3137.22   229.9 3136.93   259.9 3135.19   269.9 3134.49   279.9 3133.57
   289.9 3132.48   294.8 3132.14   299.9 3131.78   309.8 3132.12   319.9 3133.71
   329.9 3135.66   339.9 3137.26   429.9 3150.53   439.9  3152.2   449.9 3154.04
#Mann= 3 , 0 , 0
       0      .1       0   294.8    .045       0   309.8      .1       0
#XS Ineff= 2 , 0
          219.93  3137.2
Permanent Ineff=
       F       F
Bank Sta=294.8,309.8
XS Rating Curve= 0 ,0
Exp/Cntr=0.3,0.1

Type RM Length L Ch R = 1 ,14153.1 ,177.5,178.4,179.7
XS GIS Cut Line= 2
     2067571.444      383600.938     2067089.307      383714.479
#Sta/Elev= 30
       0 3142.32     9.9  3141.7    19.8 3142.36    29.7 3143.79    49.5 3147.91
    69.4 3152.78    89.2 3157.98     109 3162.64   118.9 3163.93   128.8 3163.58
   158.5 3159.25   178.3 3155.79   198.1 3151.31   217.9 3146.03   227.8 3142.72
   237.8 3137.92   247.7 3131.98   257.6 3127.55   267.5 3126.66     317 3129.17
   326.9  3128.8   346.7 3125.54     350 3125.23   356.6 3124.62     365 3124.83
   376.4 3125.94   406.2 3129.45     426 3132.33   465.6  3139.8   495.3 3146.19
#Mann= 3 , 0 , 0
       0      .1       0     350    .045       0     365      .1       0
#XS Ineff= 2 , 0
          318.35 3129.16
Permanent Ineff=
       F       F
Bank Sta=350,365
XS Rating Curve= 0 ,0
Exp/Cntr=0.3,0.1

Type RM Length L Ch R = 1 ,13974.7 ,215.8,170.4,199.2
XS GIS Cut Line= 2
     2067329.393      383486.817     2066940.219      383558.989
#Sta/Elev= 30
       0 3148.61     9.9 3145.63    19.8 3142.49    29.7 3139.14    39.6 3135.64
    49.5  3131.7    59.4  3127.4    69.3 3124.46    79.2 3124.51    89.1  3125.4
      99 3124.83   118.7 3120.83   120.1 3120.73   128.6 3120.08   135.1 3120.38
   138.5 3120.54   158.3 3122.04     188 3123.73   207.8 3125.34   227.6 3127.35
   237.5 3128.62   247.4 3130.26   277.1  3136.2   296.9 3140.45   306.8 3142.78
   326.5 3147.85   356.2 3155.92   366.1 3158.89   385.9 3165.78   395.8 3168.96
#Mann= 3 , 0 , 0
       0      .1       0   120.1    .045       0   135.1      .1       0
Bank Sta=120.1,135.1
XS Rating Curve= 0 ,0
Exp/Cntr=0.3,0.1

Type RM Length L Ch R = 1 ,13804.3 ,333.6,333.6,333.8
XS GIS Cut Line= 2
     2067310.074      383339.288     2066823.846      383372.758
#Sta/Elev= 30
       0  3136.9      10  3134.1    19.9 3130.34    29.8 3125.44    39.8 3120.75
    49.7  3118.4    59.7 3118.49    79.6  3120.7    89.5 3120.37    99.5  3118.5
   109.4    3116   113.6 3115.31   119.4 3114.35   128.6 3114.41   149.2 3115.44
   169.1 3116.04   208.9 3116.79   248.7 3117.32   278.5 3118.09   288.4 3118.73
   298.4 3120.23   308.3 3122.47   318.3    3125   338.2 3130.38   358.1 3136.02
     378 3141.98   397.9 3148.07   437.6 3160.64   477.4 3173.56   487.4 3176.14
#Mann= 3 , 0 , 0
       0      .1       0   113.6    .045       0   128.6      .1       0
Bank Sta=113.6,128.6
XS Rating Curve= 0 ,0
Exp/Cntr=0.3,0.1

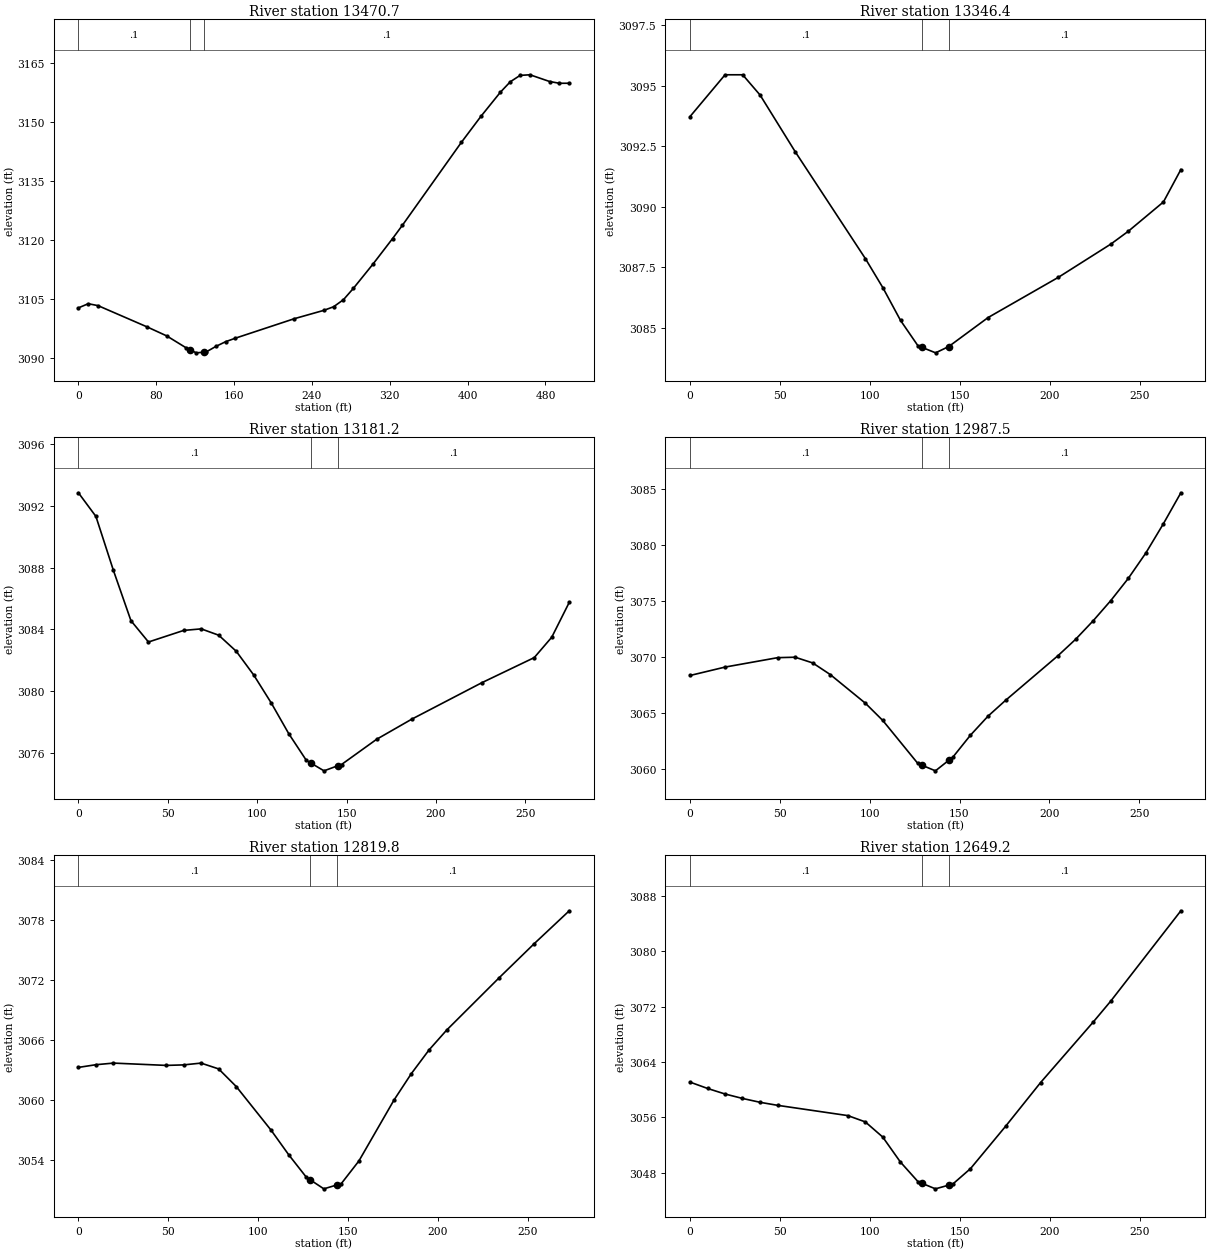
Type RM Length L Ch R = 1 ,13470.7 ,124.7,124.2,123.4
XS GIS Cut Line= 2
     2067240.518       383019.16     2066736.949      383049.321
#Sta/Elev= 30
       0 3102.69    10.1 3103.75    20.2 3103.26    70.6 3097.86    90.8 3095.57
     111  3092.5   114.4 3092.08   121.1 3091.27   129.4 3091.44   131.2 3091.48
   141.2 3092.89   151.3  3094.1   161.4    3095     222 3099.95   252.2 3102.06
   262.3 3102.98   272.4 3104.77   282.5 3107.62   302.7  3113.8   322.9  3120.3
     333 3123.68   393.5 3144.71   413.7 3151.35   433.8 3157.51   443.9 3160.14
     454 3161.76   464.1 3161.91   484.3  3160.2   494.4 3159.75   504.5 3159.76
#Mann= 3 , 0 , 0
       0      .1       0   114.4    .045       0   129.4      .1       0
Bank Sta=114.4,129.4
XS Rating Curve= 0 ,0
Exp/Cntr=0.3,0.1

Type RM Length L Ch R = 1 ,13346.4 ,171.9,165.3,158.7
XS GIS Cut Line= 3
      2067236.71        382892.6     2067100.571       382903.56
     2066964.726      382916.598
#Sta/Elev= 18
       0 3093.73    19.5 3095.46    29.3 3095.46      39 3094.62    58.5 3092.28
    97.6 3087.85   107.3 3086.65   117.1  3085.3   126.8 3084.25   128.9 3084.19
   136.6 3083.96   143.9 3084.22   165.8 3085.42   204.8 3087.08   234.1 3088.46
   243.8 3088.99   263.3  3090.2     273 3091.54
#Mann= 3 , 0 , 0
       0      .1       0   128.9    .045       0   143.9      .1       0
Bank Sta=128.9,143.9
XS Rating Curve= 0 ,0
Exp/Cntr=0.3,0.1

Type RM Length L Ch R = 1 ,13181.2 ,199.3,193.7,188.4
XS GIS Cut Line= 3
     2067187.668      382696.971     2067059.915      382747.402
     2066933.053      382799.746
#Sta/Elev= 23
       0 3092.85     9.8 3091.32    19.6 3087.82    29.4 3084.57    39.2 3083.19
    58.9 3083.94    68.7 3084.04    78.5 3083.63    88.3 3082.59    98.1 3081.05
   107.9 3079.24   117.7 3077.25   127.5 3075.53   130.1 3075.35   137.4 3074.85
   145.1 3075.18   147.2 3075.26   166.8 3076.89   186.4 3078.19   225.6 3080.55
     255 3082.18   264.8  3083.5   274.6 3085.76
#Mann= 3 , 0 , 0
       0      .1       0   130.1    .045       0   145.1      .1       0
Bank Sta=130.1,145.1
XS Rating Curve= 0 ,0
Exp/Cntr=0.3,0.1

Type RM Length L Ch R = 1 ,12987.5 ,149.6,167.6,185.7
XS GIS Cut Line= 2
     2067050.527      382517.109     2066828.102       382675.76
#Sta/Elev= 24
       0 3068.33    19.5 3069.08    48.8 3069.92    58.5 3069.96    68.3 3069.45
    78.1 3068.41    97.6 3065.86   107.3 3064.32   126.8 3060.49   129.1 3060.33
   136.6 3059.83   144.1 3060.78   146.4 3061.07   156.1 3063.01   165.9 3064.71
   175.6 3066.11   204.9 3070.11   214.7 3071.57   224.4 3073.21   234.2 3075.01
   243.9 3076.98   253.7 3079.25   263.4 3081.84   273.2 3084.62
#Mann= 3 , 0 , 0
       0      .1       0   129.1    .045       0   144.1      .1       0
Bank Sta=129.1,144.1
XS Rating Curve= 0 ,0
Exp/Cntr=0.3,0.1

Type RM Length L Ch R = 1 ,12819.8 ,164.6,170.6,176.6
XS GIS Cut Line= 3
     2067057.147       382458.08     2066922.746      382434.235
     2066788.345      382410.389
#Sta/Elev= 23
       0 3063.27     9.8 3063.54    19.5  3063.7    48.8 3063.47    58.5 3063.52
    68.2  3063.7      78 3063.12    87.8 3061.36   107.2    3057     117 3054.55
   126.8 3052.31     129 3052.05   136.5 3051.16     144 3051.56   146.2 3051.68
     156 3053.94   175.5 3060.01   185.2 3062.66     195 3065.01   204.8 3066.99
     234 3072.21   253.5 3075.61     273 3078.89
#Mann= 3 , 0 , 0
       0      .1       0     129    .045       0     144      .1       0
Bank Sta=129,144
XS Rating Curve= 0 ,0
Exp/Cntr=0.3,0.1

Type RM Length L Ch R = 1 ,12649.2 ,157.5,157.8,158
XS GIS Cut Line= 3
     2067087.703       382327.83     2066964.248      382269.596
     2066840.793      382211.363
#Sta/Elev= 21
       0 3061.08     9.8 3060.16    19.5 3059.36    29.2 3058.72      39 3058.16
    48.8 3057.72    87.8 3056.24    97.5 3055.33   107.2 3053.14     117 3049.54
   126.8  3046.7     129 3046.46   136.5 3045.66     144  3046.2   146.2 3046.36
     156 3048.58   175.5 3054.69     195 3061.02   224.2 3069.74     234 3072.78
     273 3085.83
#Mann= 3 , 0 , 0
       0      .1       0     129    .045       0     144      .1       0
Bank Sta=129,144
XS Rating Curve= 0 ,0
Exp/Cntr=0.3,0.1

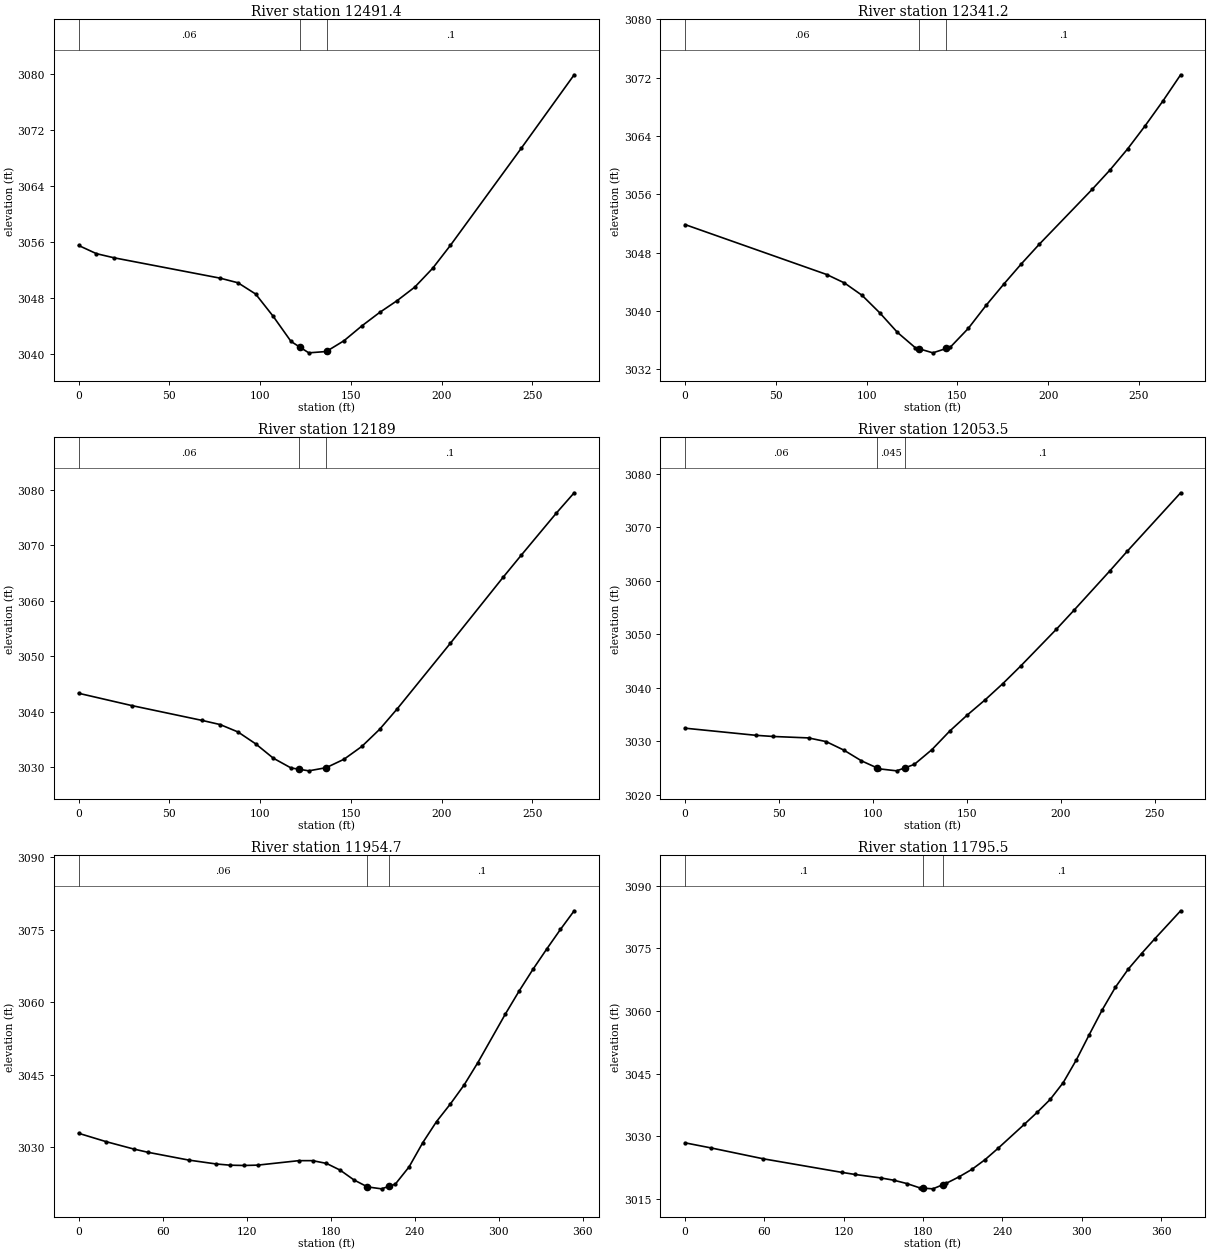
Type RM Length L Ch R = 1 ,12491.4 ,150.1,150.2,150.3
XS GIS Cut Line= 3
      2067154.96      382186.148     2067031.505      382127.914
      2066908.05      382069.681
#Sta/Elev= 21
       0 3055.55     9.8 3054.38    19.5 3053.79      78 3050.88    87.8 3050.22
    97.5 3048.62   107.2 3045.43     117 3041.85   121.9 3041.03   126.8 3040.22
   136.5 3040.41   136.9 3040.48   146.2 3041.95     156 3044.06   165.8 3045.98
   175.5 3047.68   185.2 3049.61     195 3052.28   204.8 3055.56   243.8 3069.41
     273 3079.92
#Mann= 3 , 0 , 0
       0     .06       0   121.9    .045       0   136.9      .1       0
Bank Sta=121.9,136.9
XS Rating Curve= 0 ,0
Exp/Cntr=0.3,0.1

Type RM Length L Ch R = 1 ,12341.2 ,169.1,152.2,158.7
XS GIS Cut Line= 3
     2067203.086      382046.059     2067079.631      381987.826
     2066956.176      381929.592
#Sta/Elev= 22
       0 3051.85      78    3045    87.8 3043.84    97.5 3042.14   107.2 3039.75
     117 3037.05   126.8 3034.96     129  3034.8   136.5 3034.25     144 3034.86
   146.2 3035.05     156  3037.6   165.8 3040.76   175.5 3043.66   185.2 3046.45
     195 3049.12   224.2 3056.67     234 3059.32   243.8 3062.24   253.5 3065.43
   263.2  3068.8     273 3072.41
#Mann= 3 , 0 , 0
       0     .06       0     129    .045       0     144      .1       0
Bank Sta=129,144
XS Rating Curve= 0 ,0
Exp/Cntr=0.3,0.1

Type RM Length L Ch R = 1 ,12189   ,137.9,135.5,133.4
XS GIS Cut Line= 3
     2067230.951      381852.733     2067095.318      381837.379
     2066959.684      381822.024
#Sta/Elev= 20
       0 3043.36    29.2 3041.15    68.2 3038.46      78 3037.72    87.8 3036.39
    97.5 3034.26   107.2 3031.68     117 3029.91   121.4 3029.68   126.8 3029.39
   136.4 3029.96   146.2 3031.48     156 3033.78   165.8 3036.86   175.5 3040.55
   204.8 3052.37     234 3064.31   243.8 3068.21   263.2 3075.82     273 3079.47
#Mann= 3 , 0 , 0
       0     .06       0   121.4    .045       0   136.4      .1       0
Bank Sta=121.4,136.4
XS Rating Curve= 0 ,0
Exp/Cntr=0.3,0.1

Type RM Length L Ch R = 1 ,12053.5 ,100.4,98.8,97.3
XS GIS Cut Line= 3
     2067199.307      381704.682     2067067.894      381704.682
     2066936.171      381717.738
#Sta/Elev= 23
       0 3032.43    37.6  3031.1    46.9 3030.88    65.7 3030.61    75.1 3029.92
    84.5 3028.33    93.9 3026.32     102 3025.03   103.2 3024.83   112.6 3024.45
     117 3025.01     122 3025.65   131.4 3028.42   140.9  3031.9   150.3 3034.92
   159.8 3037.76   169.2 3040.79   178.7 3044.08   197.6 3050.93     207 3054.49
     226 3061.82   235.4 3065.55   263.8 3076.48
#Mann= 3 , 0 , 0
       0     .06       0     102    .045       0     117      .1       0
Bank Sta=102,117
XS Rating Curve= 0 ,0
Exp/Cntr=0.3,0.1

Type RM Length L Ch R = 1 ,11954.7 ,168.6,159.2,148.4
XS GIS Cut Line= 2
     2067279.502      381595.232     2066926.307      381618.226
#Sta/Elev= 30
       0 3032.86    19.7 3031.12    39.3  3029.6    49.2 3028.94    78.6 3027.31
    98.3  3026.5   108.2 3026.25     118 3026.19   127.8 3026.26   157.3 3027.19
   167.1 3027.19     177 3026.62   186.8 3025.22   196.6  3023.2   206.3 3021.75
   216.3 3021.35   221.3 3021.84   226.1  3022.3     236  3025.9   245.8 3030.93
   255.6 3035.29   265.5 3038.94   275.3 3042.87   285.1  3047.5   304.8 3057.59
   314.6 3062.34   324.4  3066.8   334.3 3071.04   344.1  3075.1   353.9 3078.96
#Mann= 3 , 0 , 0
       0     .06       0   206.3    .045       0   221.3      .1       0
Bank Sta=206.3,221.3
XS Rating Curve= 0 ,0
Exp/Cntr=0.3,0.1

Type RM Length L Ch R = 1 ,11795.5 ,140,149.9,159.8
XS GIS Cut Line= 2
     2067234.318      381390.935     2066889.226      381537.457
#Sta/Elev= 29
       0 3028.48    19.7 3027.26    59.2 3024.66   118.4 3021.43   128.3 3020.93
     148 3020.09   157.9 3019.54   167.7 3018.75   177.6 3017.71     180 3017.65
   187.4 3017.48     195 3018.46   197.3 3018.76   207.2 3020.34     217 3022.14
   226.9 3024.45   236.8 3027.18   256.5 3032.87   266.4 3035.79   276.2 3038.86
   286.1  3042.9     296 3048.32   305.8 3054.38   315.7 3060.35   325.6 3065.72
   335.4 3070.08   345.3 3073.74   355.2 3077.23   374.9 3083.98
#Mann= 3 , 0 , 0
       0      .1       0     180    .045       0     195      .1       0
Bank Sta=180,195
XS Rating Curve= 0 ,0
Exp/Cntr=0.3,0.1

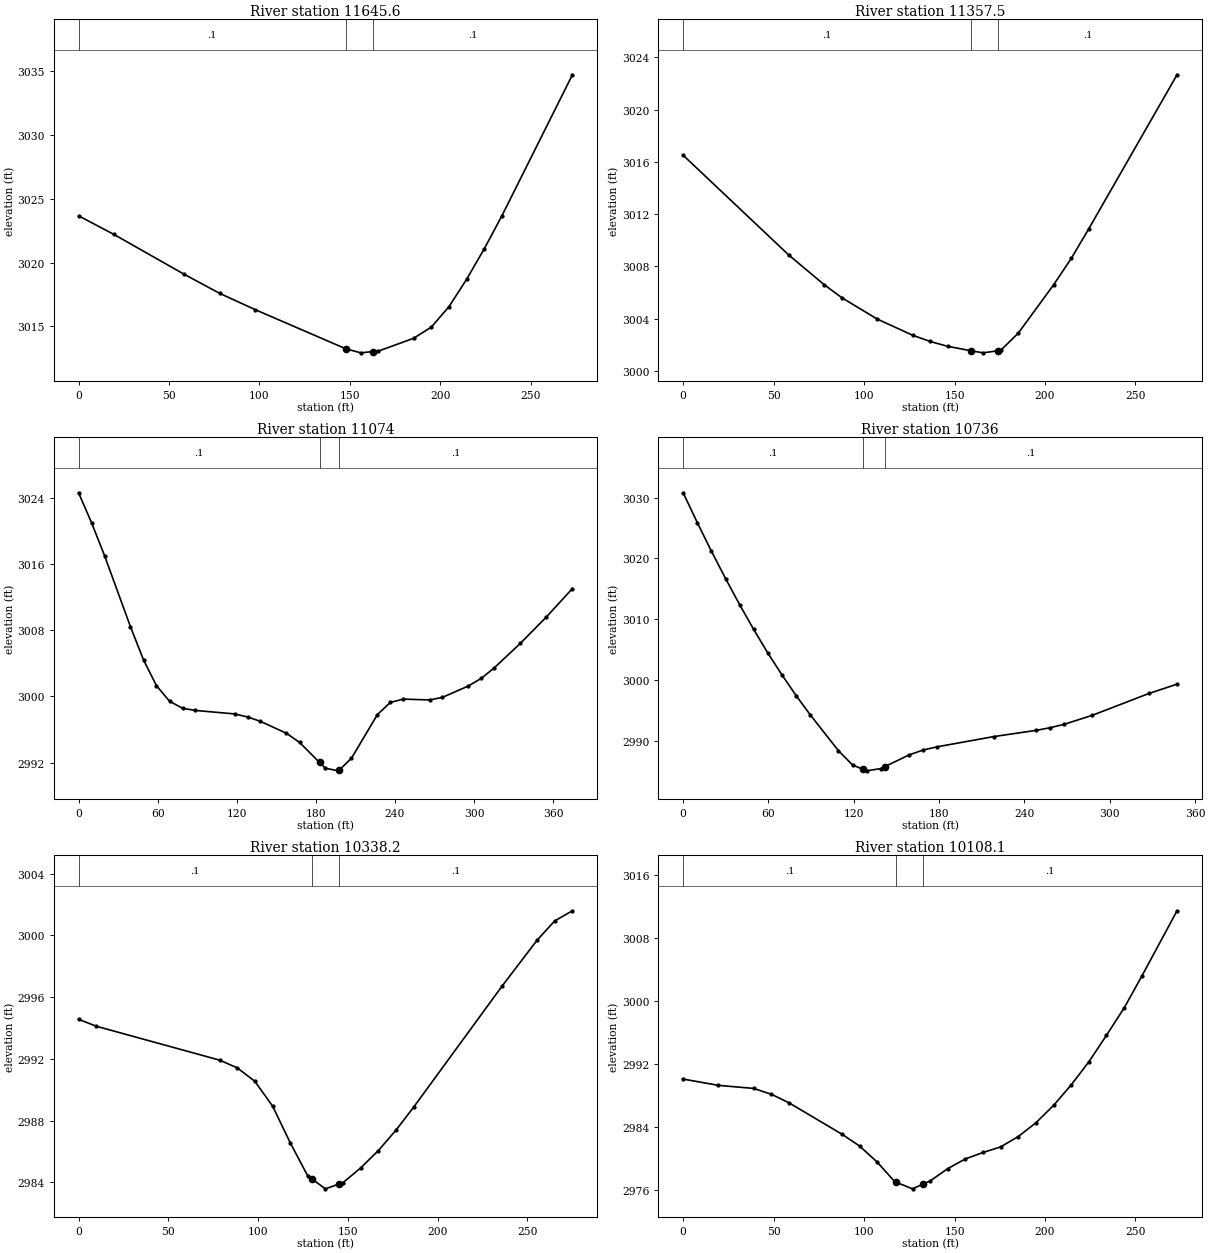
Type RM Length L Ch R = 1 ,11645.6 ,312.3,288.1,314.3
XS GIS Cut Line= 3
     2067173.993      381331.137      2067037.54      381327.546
     2066901.088      381323.955
#Sta/Elev= 16
       0 3023.67    19.5 3022.21    58.5 3019.07      78 3017.58    97.5 3016.31
   147.7 3013.23     156 3012.91   162.7 3013.01   165.8 3013.05   185.2 3014.05
     195 3014.93   204.8 3016.54   214.5 3018.68   224.2 3021.06     234 3023.66
     273 3034.74
#Mann= 3 , 0 , 0
       0      .1       0   147.7    .045       0   162.7      .1       0
Bank Sta=147.7,162.7
XS Rating Curve= 0 ,0
Exp/Cntr=0.3,0.1

Type RM Length L Ch R = 1 ,11357.5 ,274.6,283.6,292.5
XS GIS Cut Line= 3
     2067103.655      381014.978     2066976.156      381063.727
     2066848.658      381112.476
#Sta/Elev= 17
       0  3016.5    58.5 3008.85      78 3006.59    87.8 3005.59   107.2 3003.97
   126.8 3002.73   136.5 3002.25   146.2 3001.88   159.1 3001.54   165.8 3001.38
   174.1 3001.54   175.5 3001.57   185.2 3002.88   204.8 3006.59   214.5  3008.6
   224.2 3010.87     273 3022.66
#Mann= 3 , 0 , 0
       0      .1       0   159.1    .045       0   174.1      .1       0
Bank Sta=159.1,174.1
XS Rating Curve= 0 ,0
Exp/Cntr=0.3,0.1

Type RM Length L Ch R = 1 ,11074   ,339.2,338,336.9
XS GIS Cut Line= 2
     2067114.631      380800.647     2066740.195       380790.22
#Sta/Elev= 30
       0 3024.61     9.9 3020.98    19.7 3017.02    39.4 3008.41    49.3  3004.4
    59.1  3001.3      69 2999.42    78.9 2998.56    88.7  2998.3   118.3 2997.88
   128.2 2997.51     138 2996.98   157.7 2995.54   167.6 2994.44   182.8 2992.01
   187.3 2991.31   197.2    2991   197.8  2991.1     207 2992.52   226.7  2997.8
   236.6 2999.28   246.4 2999.67   266.2 2999.57     276 2999.88   295.7 3001.26
   305.6 3002.19   315.4 3003.46   335.2 3006.42   354.9 3009.61   374.6 3013.03
#Mann= 3 , 0 , 0
       0      .1       0   182.8    .045       0   197.8      .1       0
Bank Sta=182.8,197.8
XS Rating Curve= 0 ,0
Exp/Cntr=0.3,0.1

Type RM Length L Ch R = 1 ,10736   ,396,397.7,404.7
XS GIS Cut Line= 2
     2067080.929      380457.643     2066733.703      380465.637
#Sta/Elev= 26
       0 3030.78     9.9 3025.89    19.8  3021.2    29.8 3016.68    39.7 3012.38
    49.6  3008.3    59.5 3004.44    69.5 3000.82    79.4 2997.44    89.3 2994.28
   109.2 2988.36   119.1 2986.02   126.7 2985.28     129 2985.05   138.9 2985.42
   141.7 2985.73   158.8 2987.66   168.7 2988.47   178.6    2989   218.3 2990.68
   248.1  2991.7     258 2992.14   267.9  2992.7   287.8 2994.19   327.5 2997.77
   347.3 2999.31
#Mann= 3 , 0 , 0
       0      .1       0   126.7    .045       0   141.7      .1       0
Bank Sta=126.7,141.7
XS Rating Curve= 0 ,0
Exp/Cntr=0.3,0.1

Type RM Length L Ch R = 1 ,10338.2 ,220.6,230.2,239.7
XS GIS Cut Line= 2
     2067054.994      380089.041     2066780.132      380078.307
#Sta/Elev= 20
       0 2994.57     9.8 2994.12    78.6 2991.92    88.4 2991.42    98.2 2990.55
   108.1 2988.94   117.9 2986.57   127.7 2984.41     130 2984.22   137.5 2983.58
     145 2983.89   147.4 2983.99   157.2 2984.94     167 2986.06   176.8 2987.38
   186.7 2988.88   235.8  2996.7   255.4 2999.69   265.2 3000.94   275.1  3001.6
#Mann= 3 , 0 , 0
       0      .1       0     130    .045       0     145      .1       0
Bank Sta=130,145
XS Rating Curve= 0 ,0
Exp/Cntr=0.3,0.1

Type RM Length L Ch R = 1 ,10108.1 ,331.5,315.6,299.6
XS GIS Cut Line= 3
     2067097.219      379921.996     2066974.856      379861.502
     2066852.493      379801.008
#Sta/Elev= 26
       0 2990.08    19.5 2989.28      39 2988.89    48.8 2988.14    58.5 2987.06
    87.8 2983.06    97.5 2981.56   107.2 2979.53     117 2977.01   117.6 2976.96
   126.8 2976.11   132.6 2976.71   136.5 2977.11   146.2 2978.67     156 2979.92
   165.8 2980.74   175.5 2981.45   185.2 2982.76     195 2984.52   204.8 2986.74
   214.5 2989.34   224.2 2992.26     234 2995.65   243.8 2999.15   253.5 3003.17
     273  3011.5
#Mann= 3 , 0 , 0
       0      .1       0   117.6    .045       0   132.6      .1       0
Bank Sta=117.6,132.6
XS Rating Curve= 0 ,0
Exp/Cntr=0.3,0.1

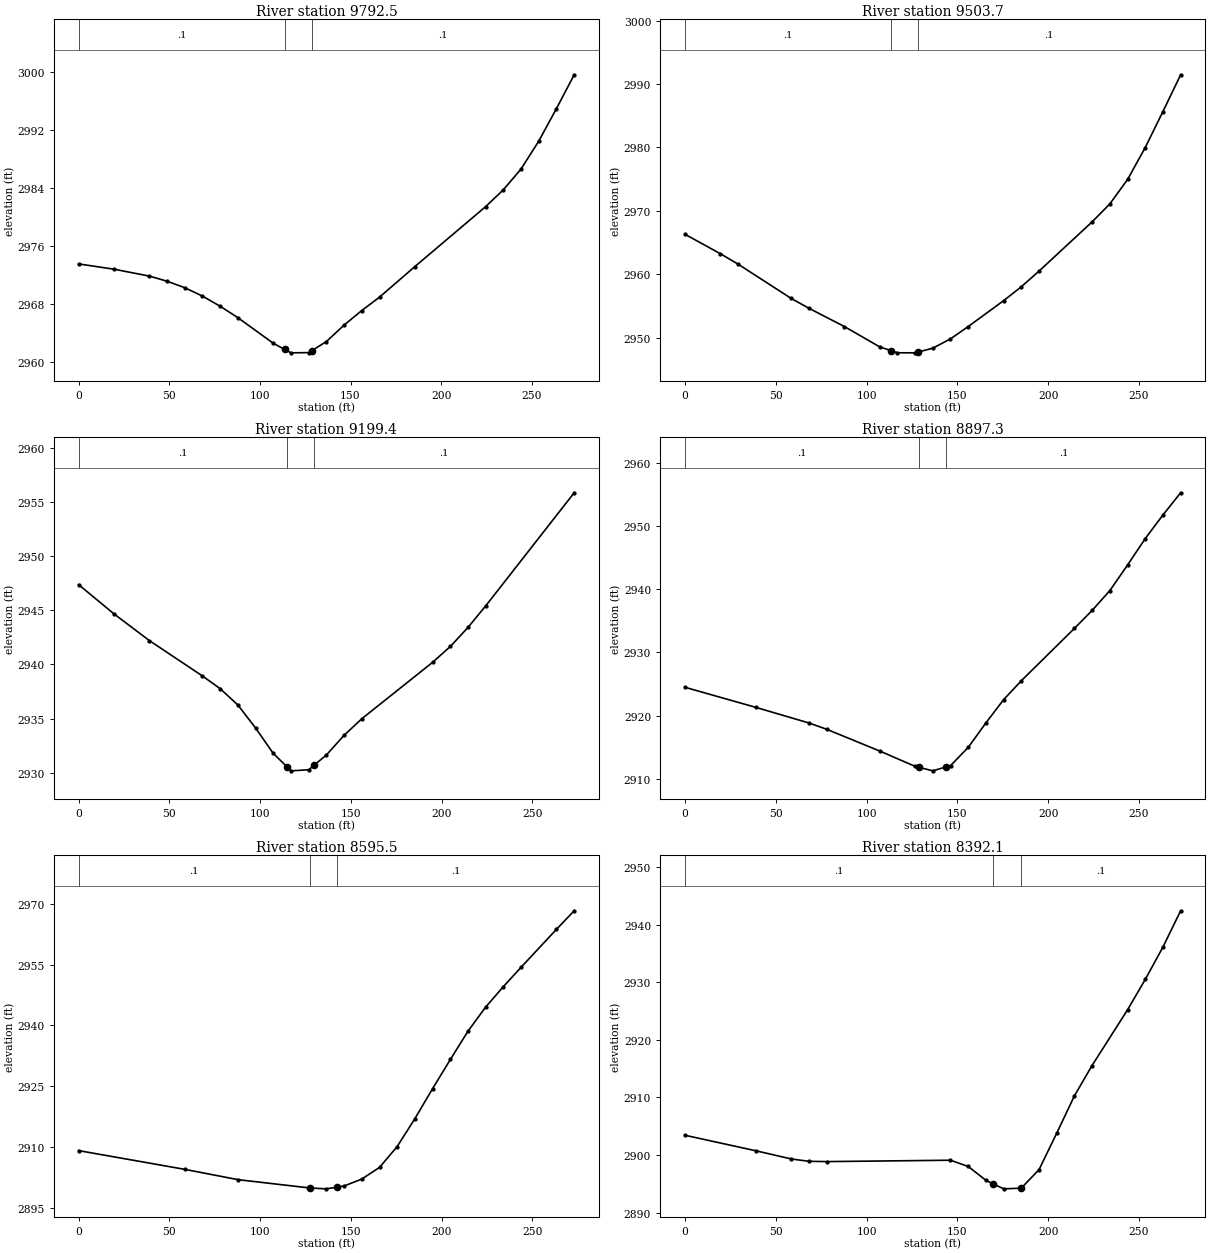
Type RM Length L Ch R = 1 ,9792.5  ,288.8,288.8,288.8
XS GIS Cut Line= 2
     2067152.321      379536.768     2066887.412       379604.27
#Sta/Elev= 24
       0 2973.55    19.5 2972.82      39 2971.87    48.8 2971.16    58.6 2970.26
    68.3 2969.11    78.1  2967.7    87.9 2966.12   107.4 2962.59   113.6 2961.75
   117.2 2961.27   126.9  2961.3   128.6 2961.56   136.7 2962.83   146.4 2965.09
   156.2 2967.11     166 2968.96   185.5 2973.18   224.6 2981.47   234.3 2983.78
   244.1 2986.66   253.8 2990.48   263.6 2994.99   273.4 2999.67
#Mann= 3 , 0 , 0
       0      .1       0   113.6    .045       0   128.6      .1       0
Bank Sta=113.6,128.6
XS Rating Curve= 0 ,0
Exp/Cntr=0.3,0.1

Type RM Length L Ch R = 1 ,9503.7  ,307.1,304.3,301.5
XS GIS Cut Line= 3
     2067069.092      379260.971     2066936.869      379294.874
     2066804.646      379328.777
#Sta/Elev= 23
       0 2966.29    19.5 2963.23    29.2 2961.59    58.5 2956.18    68.2 2954.64
    87.8 2951.75   107.2 2948.55   113.3 2947.97     117 2947.62   126.8 2947.61
   128.3 2947.73   136.5 2948.35   146.2 2949.81     156 2951.76   175.5 2955.84
   185.2 2958.02     195  2960.5   224.2 2968.25     234 2971.09   243.8 2974.96
   253.5 2979.98   263.2 2985.63     273 2991.45
#Mann= 3 , 0 , 0
       0      .1       0   113.3    .045       0   128.3      .1       0
Bank Sta=113.3,128.3
XS Rating Curve= 0 ,0
Exp/Cntr=0.3,0.1

Type RM Length L Ch R = 1 ,9199.4  ,305.9,302,297.8
XS GIS Cut Line= 3
     2066961.657      378963.732     2066834.454      379013.247
     2066707.251      379062.762
#Sta/Elev= 20
       0 2947.39    19.5 2944.68      39 2942.21    68.2 2938.94      78 2937.76
    87.8 2936.24    97.5 2934.12   107.2 2931.78   114.8 2930.53     117 2930.16
   126.8 2930.26   129.8 2930.69   136.5 2931.63   146.2 2933.44     156 2934.98
     195  2940.2   204.8 2941.67   214.5 2943.43   224.2 2945.41     273 2955.89
#Mann= 3 , 0 , 0
       0      .1       0   114.8    .045       0   129.8      .1       0
Bank Sta=114.8,129.8
XS Rating Curve= 0 ,0
Exp/Cntr=0.3,0.1

Type RM Length L Ch R = 1 ,8897.3  ,347,301.8,302.6
XS GIS Cut Line= 3
     2066784.806       378700.63     2066668.386      378771.927
     2066553.035      378844.904
#Sta/Elev= 21
       0 2924.47      39  2921.3    68.3 2918.83      78 2917.84   107.3 2914.39
   126.8 2911.97     129 2911.81   136.5 2911.27     144 2911.92   146.3 2912.11
     156 2914.98   165.8 2918.88   175.5 2922.53   185.3 2925.53   214.5 2933.79
   224.3 2936.64     234 2939.76   243.8 2943.82   253.5 2947.98   263.3 2951.73
     273 2955.22
#Mann= 3 , 0 , 0
       0      .1       0     129    .045       0     144      .1       0
Bank Sta=129,144
XS Rating Curve= 0 ,0
Exp/Cntr=0.3,0.1

Type RM Length L Ch R = 1 ,8595.5  ,197.7,203.5,209.1
XS GIS Cut Line= 3
     2066642.069      378444.325     2066523.211      378511.444
     2066404.353      378578.564
#Sta/Elev= 19
       0 2909.05    58.5 2904.42    87.8 2901.88   127.4 2899.82   136.5 2899.61
   142.4 2900.03   146.2 2900.31     156 2902.02   165.8 2904.92   175.5 2910.06
   185.2 2916.91     195 2924.35   204.8 2931.56   214.5 2938.54   224.2 2944.48
     234 2949.55   243.8 2954.35   263.2 2963.68     273 2968.28
#Mann= 3 , 0 , 0
       0      .1       0   127.4    .045       0   142.4      .1       0
Bank Sta=127.4,142.4
XS Rating Curve= 0 ,0
Exp/Cntr=0.3,0.1

Type RM Length L Ch R = 1 ,8392.1  ,253.9,255.7,257.6
XS GIS Cut Line= 3
     2066596.967      378290.061     2066464.696      378323.777
     2066332.426      378357.493
#Sta/Elev= 20
       0 2903.42      39 2900.73    58.5 2899.31    68.2  2898.9      78 2898.85
   146.2 2899.09     156    2898   165.8 2895.58   169.8 2894.97   175.5 2894.12
   184.8 2894.23   185.2 2894.24     195 2897.46   204.8 2903.83   214.5 2910.28
   224.2 2915.54   243.8 2925.24   253.5 2930.48   263.2 2936.08     273 2942.41
#Mann= 3 , 0 , 0
       0      .1       0   169.8    .045       0   184.8      .1       0
Bank Sta=169.8,184.8
XS Rating Curve= 0 ,0
Exp/Cntr=0.3,0.1