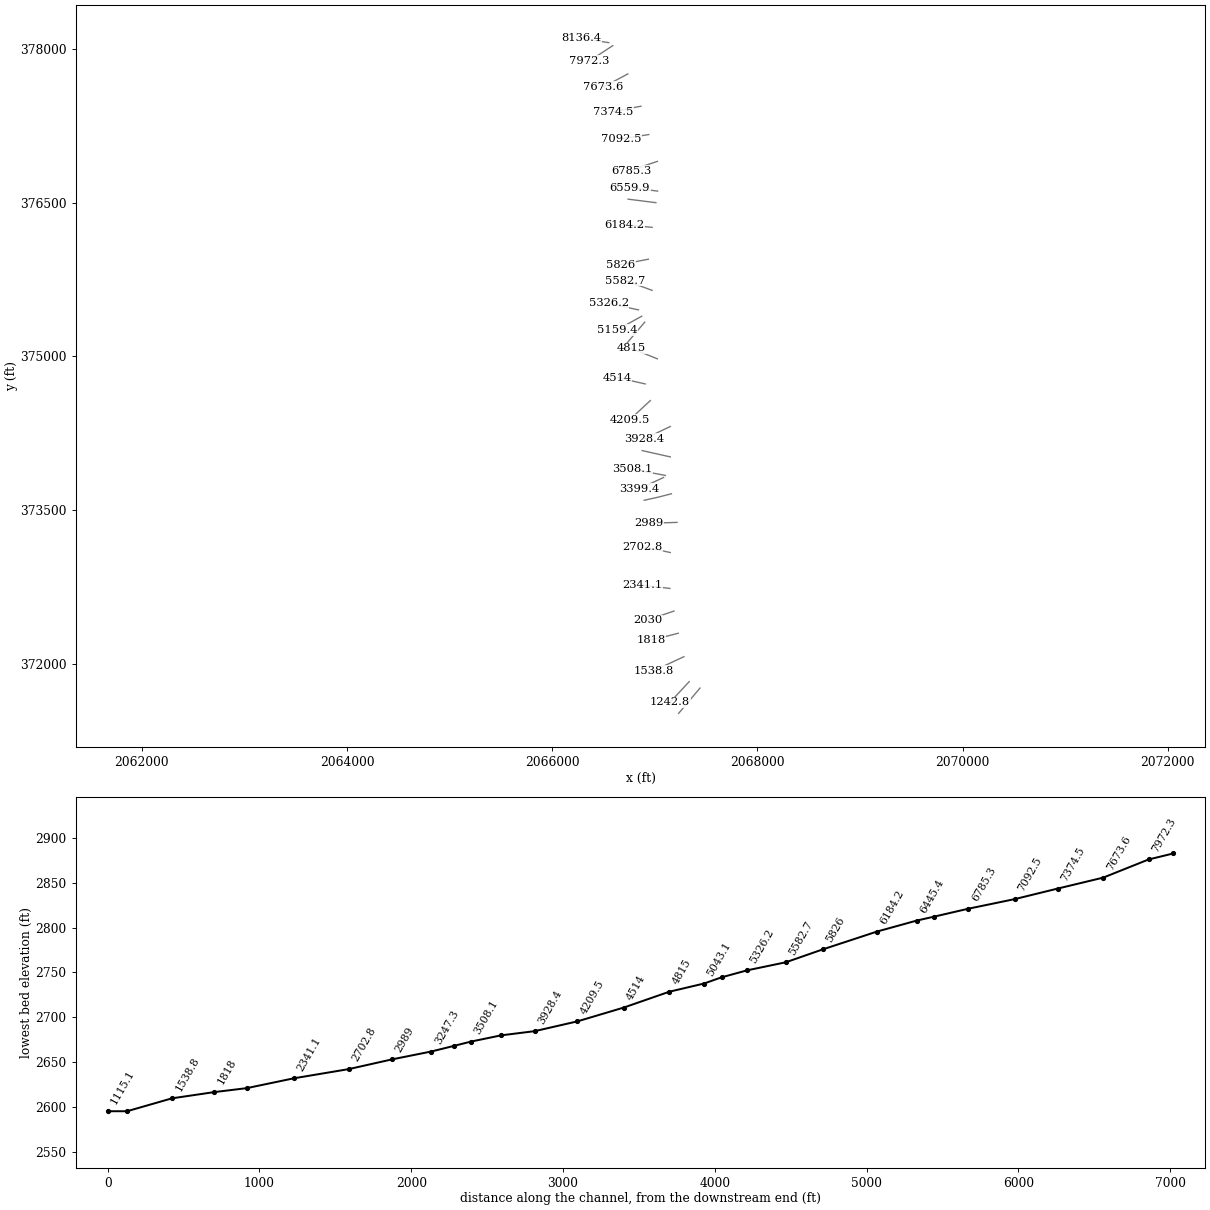
HEC-RAS study BrownCreek.prj: BrownCreek

--- BrownCreek.g01 (geometry) --- (continued)

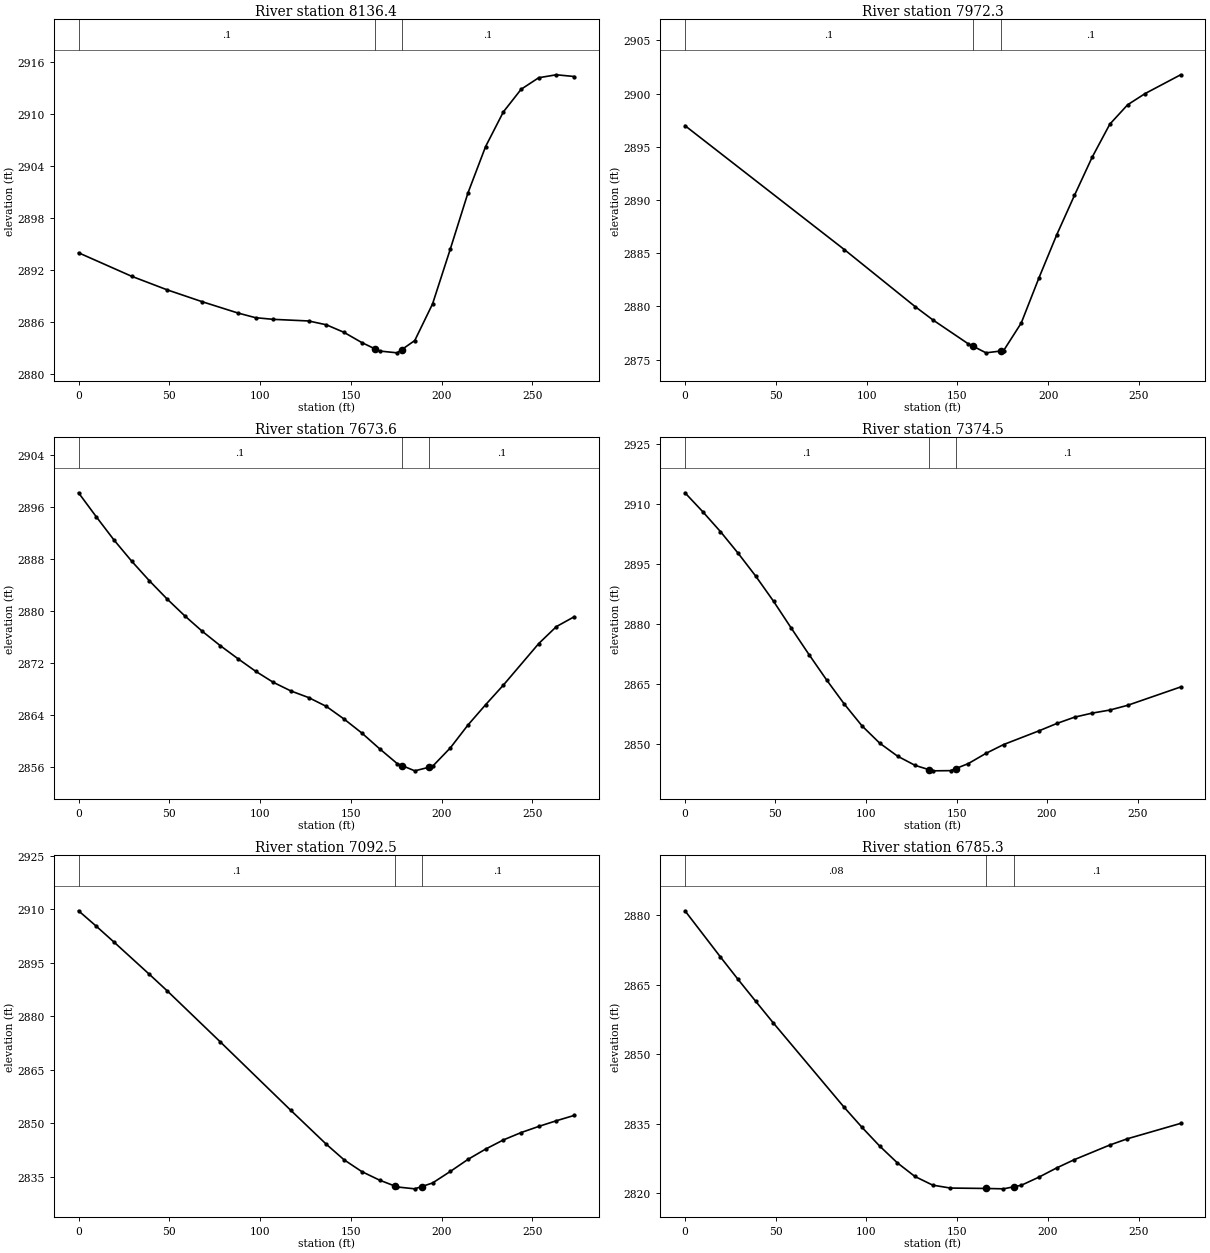
Type RM Length L Ch R = 1 ,8136.4  ,146.4,164.1,181.8
XS GIS Cut Line= 3
      2066551.42      378058.858      2066416.55      378079.887
     2066281.679      378100.916
#Sta/Elev= 25
       0 2893.97    29.2 2891.26    48.8 2889.69    68.2 2888.31    87.8 2887.01
    97.5 2886.47   107.2 2886.28   126.8 2886.09   136.5 2885.65   146.2 2884.78
     156  2883.6   163.1 2882.89   165.8 2882.62   175.5 2882.41   178.1 2882.79
   185.2 2883.83     195 2888.06   204.8 2894.41   214.5 2900.88   224.2 2906.23
     234 2910.24   243.8 2912.86   253.5 2914.19   263.2 2914.53     273 2914.33
#Mann= 3 , 0 , 0
       0      .1       0   163.1    .045       0   178.1      .1       0
Bank Sta=163.1,178.1
XS Rating Curve= 0 ,0
Exp/Cntr=0.3,0.1

Type RM Length L Ch R = 1 ,7972.3  ,300.9,298.7,296.6
XS GIS Cut Line= 3
     2066590.199      378029.665     2066476.164      377954.643
      2066362.13       377879.62
#Sta/Elev= 18
       0 2896.99    87.8 2885.34   126.8 2879.98   136.5 2878.74     156 2876.49
   158.8 2876.25   165.8 2875.64   173.8 2875.81   175.5 2875.85   185.2 2878.44
     195  2882.7   204.8 2886.75   214.5 2890.43   224.2    2894     234 2897.13
   243.8 2898.95   253.5 2900.01     273 2901.77
#Mann= 3 , 0 , 0
       0      .1       0   158.8    .045       0   173.8      .1       0
Bank Sta=158.8,173.8
XS Rating Curve= 0 ,0
Exp/Cntr=0.3,0.1

Type RM Length L Ch R = 1 ,7673.6  ,305.9,299.1,292.3
XS GIS Cut Line= 3
     2066737.691      377754.022     2066617.114      377690.042
     2066496.537      377626.062
#Sta/Elev= 30
       0 2898.19     9.8  2894.5    19.5 2890.95    29.2 2887.71      39 2884.68
    48.8 2881.87    58.5 2879.29    68.2  2876.9      78 2874.72    87.8  2872.7
    97.5 2870.78   107.2 2869.08     117 2867.74   126.8 2866.72   136.5 2865.37
   146.2 2863.44     156 2861.29   165.8 2858.87   175.5 2856.59   178.2 2856.28
   185.2 2855.47   193.2 2856.03     195 2856.16   204.8    2859   214.5 2862.51
   224.2 2865.62     234 2868.64   253.5 2875.03   263.2 2877.63     273 2879.14
#Mann= 3 , 0 , 0
       0      .1       0   178.2    .045       0   193.2      .1       0
Bank Sta=178.2,193.2
XS Rating Curve= 0 ,0
Exp/Cntr=0.3,0.1

Type RM Length L Ch R = 1 ,7374.5  ,282.8,281.9,281
XS GIS Cut Line= 2
     2066865.299      377439.517     2066596.565      377386.868
#Sta/Elev= 28
       0 2912.86     9.8 2908.14    19.6 2903.15    29.3 2897.78    39.1 2892.01
    48.9 2885.75    58.7 2879.03    68.5 2872.42    78.2 2866.09      88 2860.04
    97.8 2854.58   107.6 2850.25   117.4 2847.02   127.1 2844.71   134.6 2843.66
   136.9 2843.34   146.7 2843.39   149.6 2843.91   156.5 2845.15   166.3 2847.72
     176 2849.91   195.6 2853.35   205.4 2855.18   215.2 2856.76   224.9 2857.77
   234.7 2858.54   244.5 2859.72   273.8 2864.31
#Mann= 3 , 0 , 0
       0      .1       0   134.6    .045       0   149.6      .1       0
Bank Sta=134.6,149.6
XS Rating Curve= 0 ,0
Exp/Cntr=0.3,0.1

Type RM Length L Ch R = 1 ,7092.5  ,302.7,307.2,311.8
XS GIS Cut Line= 3
     2066941.612      377163.014     2066806.735      377142.033
     2066671.857      377121.051
#Sta/Elev= 24
       0 2909.57     9.8 2905.24    19.5 2900.82      39 2891.78    48.8 2887.16
      78 2872.88     117 2853.62   136.5 2844.15   146.2 2839.82     156  2836.5
   165.8  2834.1   174.1 2832.47   175.5 2832.19   185.2 2831.66   189.1 2832.31
     195  2833.3   204.8 2836.54   214.5 2839.91   224.2 2842.79     234 2845.36
   243.8 2847.43   253.5 2849.15   263.2 2850.74     273 2852.23
#Mann= 3 , 0 , 0
       0      .1       0   174.1    .045       0   189.1      .1       0
Bank Sta=174.1,189.1
XS Rating Curve= 0 ,0
Exp/Cntr=0.3,0.1

Type RM Length L Ch R = 1 ,6785.3  ,236.5,225.3,214.2
XS GIS Cut Line= 3
     2067024.949      376901.368     2066895.421      376858.361
     2066767.411       376810.66
#Sta/Elev= 22
       0    2881    19.5 2871.04    29.2  2866.2      39 2861.43    48.7 2856.76
    87.7 2838.55    97.5 2834.23   107.2  2830.2     117 2826.55   126.7  2823.6
   136.5 2821.73   146.2  2821.1   166.1 2821.01   175.5 2820.93   181.1 2821.37
   185.3  2821.7     195 2823.45   204.8 2825.45   214.5 2827.23   234.1  2830.4
   243.8 2831.75   273.1 2835.07
#Mann= 3 , 0 , 0
       0     .08       0   166.1    .045       0   181.1      .1       0
Bank Sta=166.1,181.1
XS Rating Curve= 0 ,0
Exp/Cntr=0.3,0.1

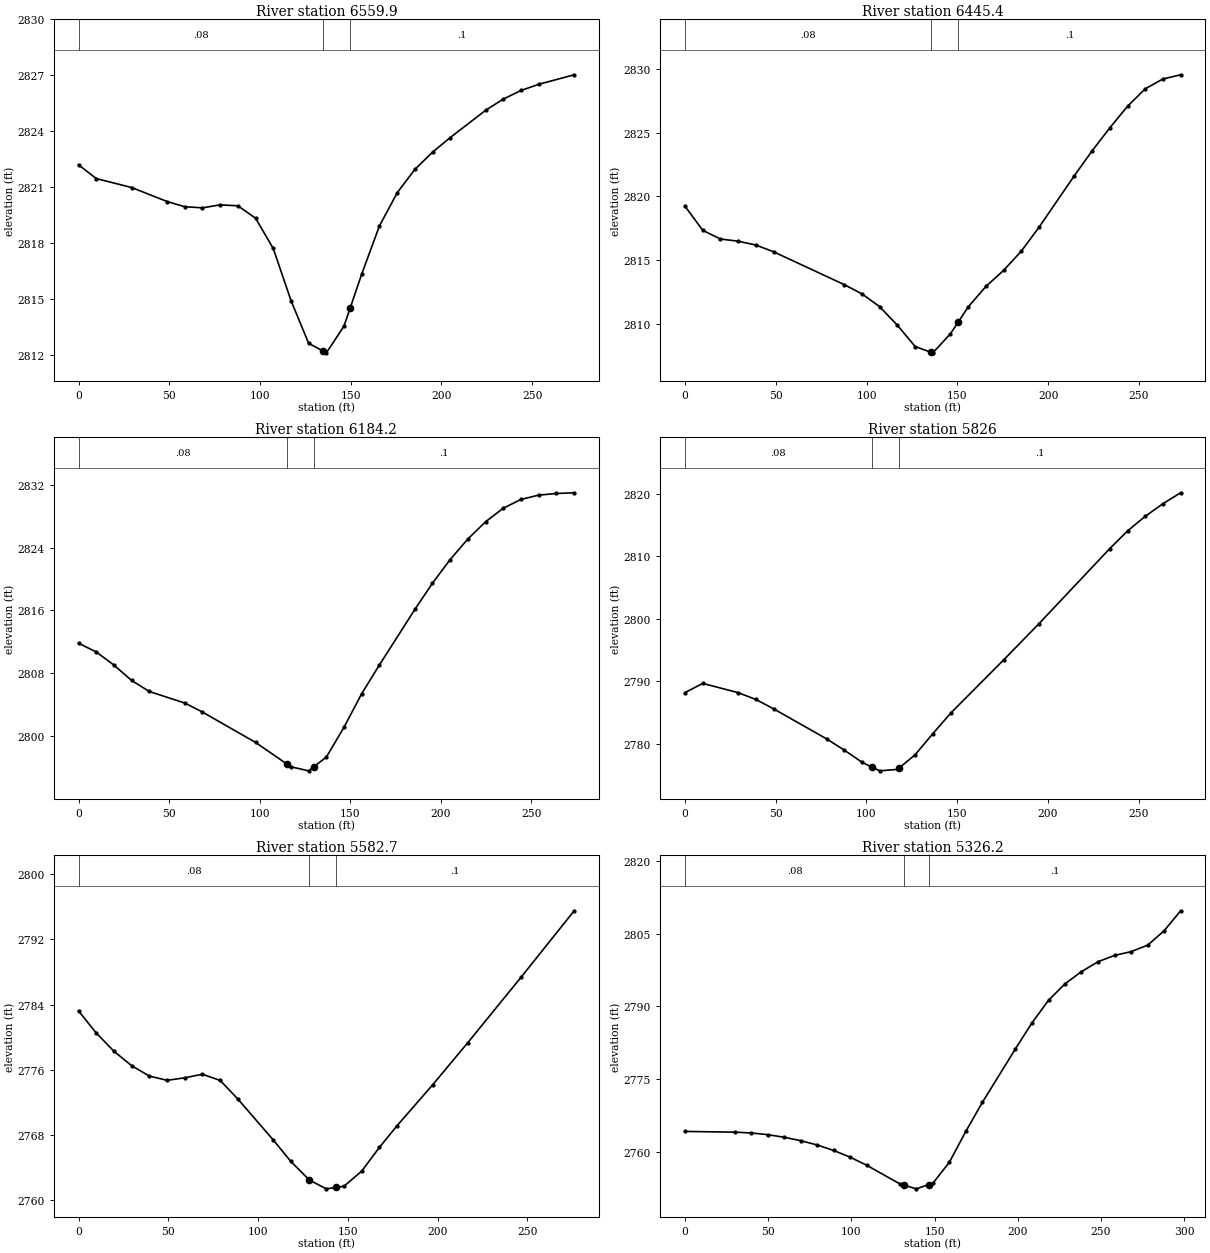
Type RM Length L Ch R = 1 ,6559.9  ,114.4,114.5,114.6
XS GIS Cut Line= 2
     2067027.475       376611.85     2066756.584      376646.767
#Sta/Elev= 27
       0  2822.2     9.8 2821.46    29.3 2820.98    48.8 2820.23    58.5 2819.95
    68.3 2819.89      78 2820.05    87.8    2820    97.6 2819.33   107.3 2817.71
   117.1 2814.91   126.8 2812.62   134.7 2812.21   136.6 2812.11   146.3 2813.55
   149.7 2814.52   156.1 2816.35   165.8 2818.92   175.6  2820.7   185.3 2821.95
   195.1 2822.88   204.8 2823.66   224.4 2825.13   234.1 2825.73   243.9 2826.19
   253.6 2826.52   273.1 2827.03
#Mann= 3 , 0 , 0
       0     .08       0   134.7    .045       0   149.7      .1       0
Bank Sta=134.7,149.7
XS Rating Curve= 0 ,0
Exp/Cntr=0.3,0.1

Type RM Length L Ch R = 1 ,6445.4  ,278.3,261.3,259.7
XS GIS Cut Line= 3
     2067010.738      376499.168     2066875.313      376516.261
     2066739.887      376533.353
#Sta/Elev= 27
       0 2819.23     9.8 2817.34    19.5 2816.66    29.2 2816.49      39 2816.19
    48.8 2815.66    87.8 2813.08    97.5 2812.36   107.2 2811.36     117  2809.9
   126.8 2808.23   135.4 2807.79   136.5 2807.74   146.2 2809.23   150.4 2810.13
     156 2811.34   165.8 2812.95   175.5  2814.2   185.2  2815.7     195 2817.58
   214.5 2821.63   224.2 2823.56     234 2825.37   243.8 2827.07   253.5 2828.43
   263.2  2829.2     273 2829.53
#Mann= 3 , 0 , 0
       0     .08       0   135.4    .045       0   150.4      .1       0
Bank Sta=135.4,150.4
XS Rating Curve= 0 ,0
Exp/Cntr=0.3,0.1

Type RM Length L Ch R = 1 ,6184.2  ,351.7,358.2,364.7
XS GIS Cut Line= 2
     2066974.223      376258.769     2066701.703      376284.708
#Sta/Elev= 26
       0 2811.82     9.8 2810.71    19.6 2809.03    29.3 2807.08    39.1 2805.67
    58.7  2804.2    68.4 2803.06    97.8 2799.18   114.9 2796.46   117.3 2796.08
   127.1 2795.56   129.9 2796.06   136.9 2797.31   146.6 2801.09   156.4 2805.38
   166.2 2809.05   185.8 2816.13   195.5 2819.46   205.3 2822.48   215.1 2825.11
   224.9  2827.3   234.6 2829.02   244.4 2830.14   254.2 2830.69     264  2830.9
   273.8 2830.99
#Mann= 3 , 0 , 0
       0     .08       0   114.9    .045       0   129.9      .1       0
Bank Sta=114.9,129.9
XS Rating Curve= 0 ,0
Exp/Cntr=0.3,0.1

Type RM Length L Ch R = 1 ,5826    ,256,243.3,230.6
XS GIS Cut Line= 2
     2066937.571      375948.156     2066669.476      375895.939
#Sta/Elev= 22
       0 2788.22     9.8 2789.68    29.3  2788.2      39 2787.12    48.8 2785.62
      78 2780.81    87.8    2779    97.6 2777.06   102.9  2776.3   107.3 2775.69
   117.1 2775.92   117.9 2776.12   126.8 2778.26   136.6 2781.65   146.3 2784.89
   175.6 2793.45   195.1 2799.26   234.1 2811.27   243.9  2814.1   253.6 2816.42
   263.4 2818.45   273.1 2820.19
#Mann= 3 , 0 , 0
       0     .08       0   102.9    .045       0   117.9      .1       0
Bank Sta=102.9,117.9
XS Rating Curve= 0 ,0
Exp/Cntr=0.3,0.1

Type RM Length L Ch R = 1 ,5582.7  ,253.3,256.5,259.7
XS GIS Cut Line= 2
     2066973.786       375644.61     2066714.587      375739.655
#Sta/Elev= 23
       0 2783.22     9.9  2780.5    19.7 2778.27    29.6 2776.49    39.4 2775.22
    49.3 2774.69    59.2    2775      69 2775.44    78.9 2774.68    88.7 2772.41
   108.5 2767.36   118.3 2764.72   128.6 2762.44     138 2761.36   143.6 2761.54
   147.9 2761.68   157.8 2763.55   167.6 2766.45   177.5 2769.13   197.2 2774.12
   216.9 2779.33   246.5 2787.35   276.1 2795.52
#Mann= 3 , 0 , 0
       0     .08       0   128.6    .045       0   143.6      .1       0
Bank Sta=128.6,143.6
XS Rating Curve= 0 ,0
Exp/Cntr=0.3,0.1

Type RM Length L Ch R = 1 ,5326.2  ,150.6,166.8,183
XS GIS Cut Line= 2
     2066840.904      375454.345     2066549.615      375516.839
#Sta/Elev= 29
       0 2764.19    29.8 2764.04    39.7 2763.88    49.6 2763.53    59.6 2762.99
    69.5 2762.29    79.4  2761.4    89.4 2760.26    99.3 2758.87   109.2 2757.21
   129.1 2753.37   131.6 2753.11     139 2752.34   146.6 2753.23     149  2753.5
   158.9 2757.83   168.8 2764.21   178.8 2770.23   198.6 2781.23   208.5 2786.58
   218.5 2791.26   228.4 2794.66   238.3 2797.18   248.3 2799.23   258.2 2800.53
   268.1  2801.3   278.1 2802.64     288 2805.62   297.9 2809.74
#Mann= 3 , 0 , 0
       0     .08       0   131.6    .045       0   146.6      .1       0
Bank Sta=131.6,146.6
XS Rating Curve= 0 ,0
Exp/Cntr=0.3,0.1

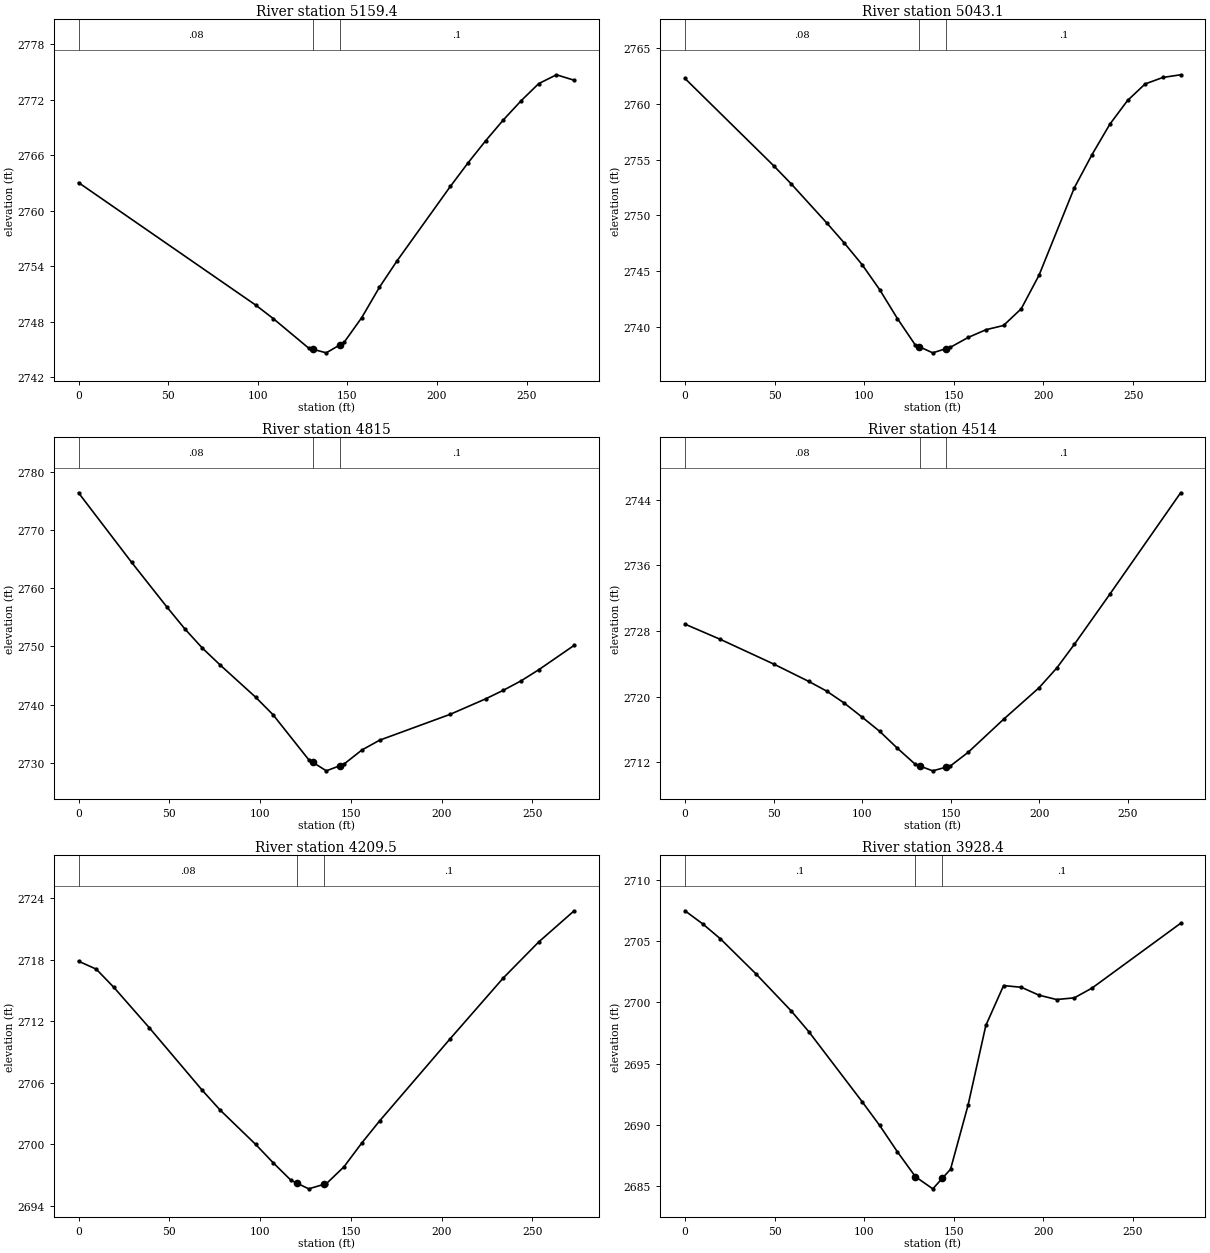
Type RM Length L Ch R = 1 ,5159.4  ,108.1,116.3,124.5
XS GIS Cut Line= 2
     2066872.463      375392.325     2066630.481      375258.574
#Sta/Elev= 19
       0 2763.04    98.8  2749.8   108.6 2748.34   128.4 2745.14   130.7 2745.02
   138.2 2744.63   145.7 2745.48   148.1 2745.75     158 2748.44   167.9 2751.73
   177.7 2754.58   207.4 2762.62   217.2 2765.15   227.1 2767.56     237 2769.82
   246.9 2771.89   256.7 2773.74   266.6  2774.7   276.5 2774.11
#Mann= 3 , 0 , 0
       0     .08       0   130.7    .045       0   145.7      .1       0
Bank Sta=130.7,145.7
XS Rating Curve= 0 ,0
Exp/Cntr=0.3,0.1

Type RM Length L Ch R = 1 ,5043.1  ,256.6,228.1,199.6
XS GIS Cut Line= 2
     2066902.143      375334.589     2066723.426      375123.626
#Sta/Elev= 25
       0 2762.27    49.4 2754.47    59.2 2752.84      79 2749.35    88.9 2747.53
    98.8  2745.6   108.6 2743.36   118.5 2740.77   128.4 2738.42   130.7 2738.25
   138.2  2737.7   145.7 2738.08   148.1  2738.2     158 2739.08   167.9 2739.77
   177.7 2740.15   187.6 2741.65   197.5 2744.65   217.2 2752.48   227.1 2755.46
     237 2758.17   246.9  2760.3   256.7 2761.78   266.6 2762.36   276.5  2762.6
#Mann= 3 , 0 , 0
       0     .08       0   130.7    .045       0   145.7      .1       0
Bank Sta=130.7,145.7
XS Rating Curve= 0 ,0
Exp/Cntr=0.3,0.1

Type RM Length L Ch R = 1 ,4815    ,297.1,301,304.9
XS GIS Cut Line= 2
     2067024.348      374977.288     2066771.202      375079.494
#Sta/Elev= 21
       0 2776.39    29.2 2764.46    48.8 2756.72    58.5 2753.03    68.2 2749.71
      78 2746.81    97.5 2741.29   107.2 2738.24   126.8 2730.53     129 2730.09
   136.5 2728.62     144 2729.51   146.2 2729.77     156 2732.18   165.8 2733.88
   204.8 2738.34   224.2 2740.98     234 2742.46   243.8 2744.09   253.5 2745.99
     273 2750.18
#Mann= 3 , 0 , 0
       0     .08       0     129    .045       0     144      .1       0
Bank Sta=129,144
XS Rating Curve= 0 ,0
Exp/Cntr=0.3,0.1

Type RM Length L Ch R = 1 ,4514    ,282.5,304.5,326.5
XS GIS Cut Line= 2
     2066906.483      374732.399     2066633.722      374794.355
#Sta/Elev= 21
       0 2728.84      20 2726.98      50 2723.98    69.9 2721.85    79.9 2720.68
    89.9 2719.21    99.9 2717.51   109.9 2715.76   119.9  2713.7   129.9 2711.76
   132.4 2711.55   139.8 2710.95   147.4  2711.4   149.8 2711.55   159.8 2713.21
   179.8 2717.24   199.8 2721.08   209.8 2723.49   219.8  2726.4   239.8 2732.51
   279.7 2744.86
#Mann= 3 , 0 , 0
       0     .08       0   132.4    .045       0   147.4      .1       0
Bank Sta=132.4,147.4
XS Rating Curve= 0 ,0
Exp/Cntr=0.3,0.1

Type RM Length L Ch R = 1 ,4209.5  ,287.9,281,274.2
XS GIS Cut Line= 3
     2066956.714      374570.005      2066856.51      374477.315
     2066756.305      374384.626
#Sta/Elev= 20
       0 2717.88     9.8  2717.1    19.5 2715.32      39 2711.38    68.2 2705.27
      78 2703.35    97.5 2700.01   107.2 2698.21     117  2696.5   120.4 2696.21
   126.8 2695.66   135.4 2696.11   136.5 2696.16   146.2 2697.81     156 2700.13
   165.8 2702.28   204.8 2710.33     234 2716.25   253.5 2719.76     273  2722.8
#Mann= 3 , 0 , 0
       0     .08       0   120.4    .045       0   135.4      .1       0
Bank Sta=120.4,135.4
XS Rating Curve= 0 ,0
Exp/Cntr=0.3,0.1

Type RM Length L Ch R = 1 ,3928.4  ,237,221.4,206
XS GIS Cut Line= 2
     2067150.937       374317.53     2066901.312      374198.474
#Sta/Elev= 22
       0 2707.46     9.9 2706.39    19.8 2705.17    39.5 2702.33    59.3 2699.29
    69.1  2697.6    98.8  2691.9   108.6 2689.96   118.5 2687.81   128.6 2685.77
   138.3 2684.78   143.6 2685.64   148.2 2686.38     158 2691.62   167.9 2698.11
   177.8 2701.36   187.7 2701.22   197.5 2700.58   207.4 2700.22   217.3 2700.36
   227.2 2701.16   276.6 2706.44
#Mann= 3 , 0 , 0
       0      .1       0   128.6    .045       0   143.6      .1       0
Bank Sta=128.6,143.6
XS Rating Curve= 0 ,0
Exp/Cntr=0.3,0.1

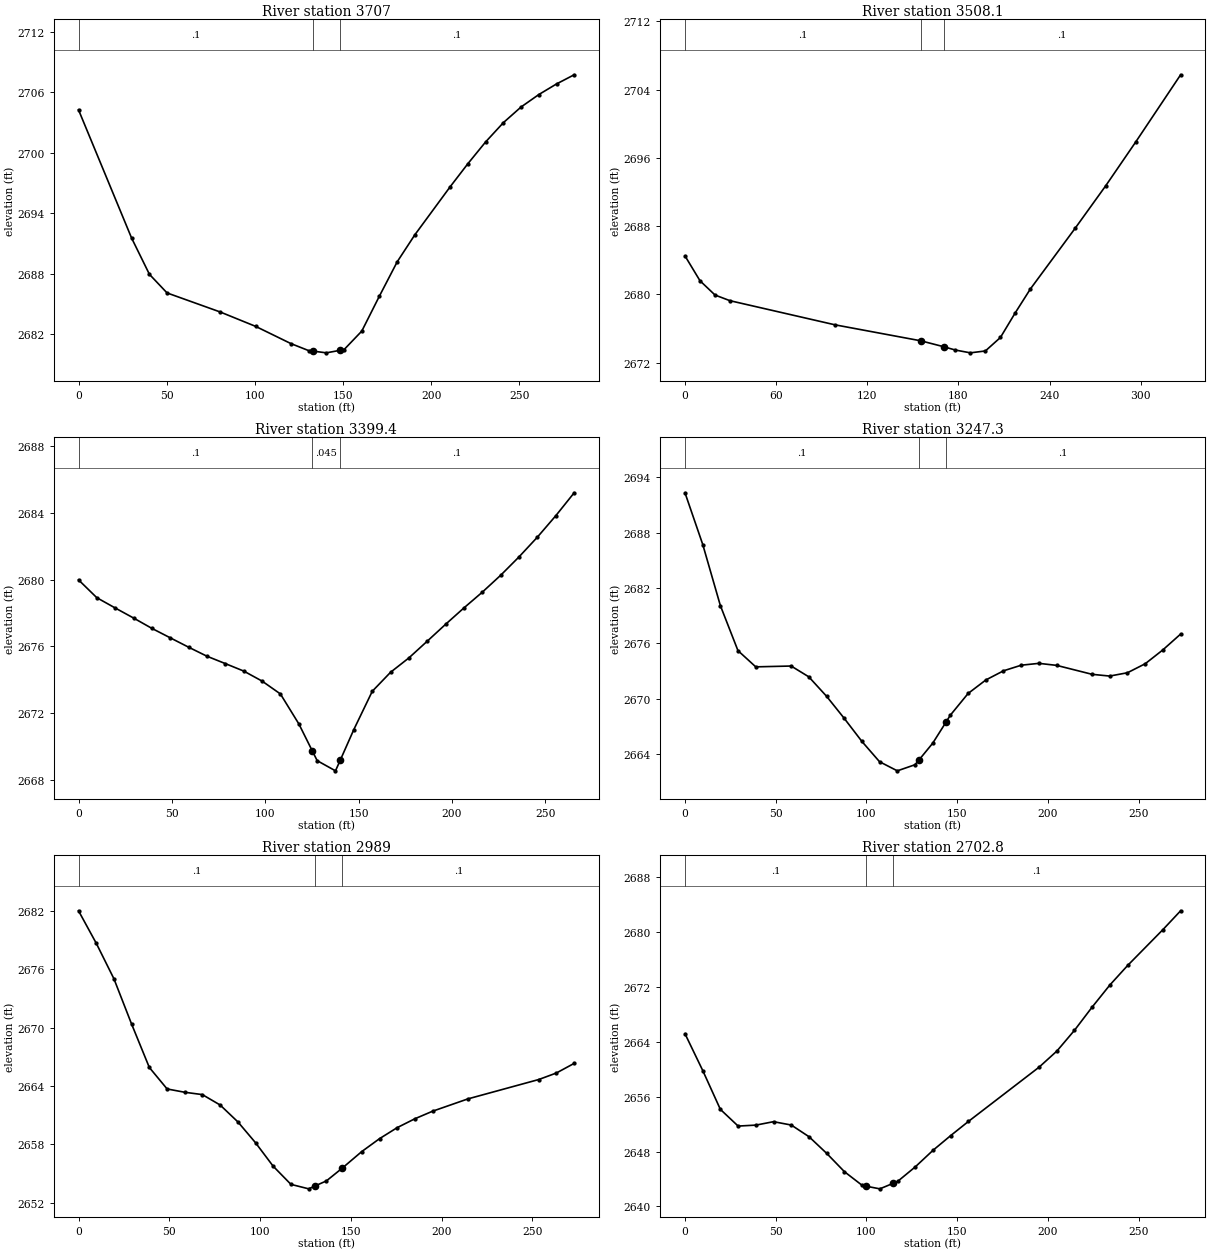
Type RM Length L Ch R = 1 ,3707    ,197.9,199,199.7
XS GIS Cut Line= 2
     2067151.453      374021.103     2066877.232      374082.562
#Sta/Elev= 24
       0 2704.26    30.1 2691.52    40.2 2687.92    50.2 2686.07    80.3 2684.18
   100.4 2682.75   120.4 2681.04   130.5 2680.34     133 2680.29   140.5 2680.12
     148 2680.36   150.6 2680.45   160.6 2682.28   170.6 2685.76   180.7 2689.17
   190.7 2691.85   210.8 2696.64   220.8 2698.92   230.8 2701.07   240.9 2702.99
   250.9 2704.54     261 2705.78     271 2706.83     281 2707.74
#Mann= 3 , 0 , 0
       0      .1       0     133    .045       0     148      .1       0
Bank Sta=133,148
XS Rating Curve= 0 ,0
Exp/Cntr=0.3,0.1

Type RM Length L Ch R = 1 ,3508.1  ,94.7,108.7,122.6
XS GIS Cut Line= 2
     2067103.729      373840.889     2066782.979      373900.084
#Sta/Elev= 17
       0 2684.52     9.9  2681.6    19.8 2679.93    29.6 2679.27    98.8 2676.44
   155.2 2674.57   170.2 2673.88   177.9 2673.49   187.8 2673.16   197.7 2673.38
   207.6 2674.96   217.4 2677.86   227.3 2680.64     257 2687.81   276.8 2692.71
   296.5 2697.83   326.2 2705.74
#Mann= 3 , 0 , 0
       0      .1       0   155.2    .045       0   170.2      .1       0
Bank Sta=155.2,170.2
XS Rating Curve= 0 ,0
Exp/Cntr=0.3,0.1

Type RM Length L Ch R = 1 ,3399.4  ,156.2,152.1,147.2
XS GIS Cut Line= 2
     2067086.457      373820.755     2066845.451       373709.62
#Sta/Elev= 30
       0 2679.98     9.8 2678.91    19.7 2678.29    29.5 2677.69    39.3 2677.07
    49.2  2676.5      59 2675.94    68.8  2675.4    78.6 2674.96    88.5 2674.51
    98.3 2673.91   108.1 2673.14     118 2671.34   125.2 2669.72   127.8 2669.14
   137.6 2668.53   140.2 2669.18   147.4    2671   157.3  2673.3   167.1 2674.44
   176.9  2675.3   186.8 2676.31   196.6 2677.32   206.4  2678.3   216.2 2679.24
   226.1 2680.26   235.9 2681.36   245.7 2682.54   255.6 2683.83   265.4  2685.2
#Mann= 3 , 0 , 0
       0      .1       0   125.2    .045       0   140.2      .1       0
Bank Sta=125.2,140.2
XS Rating Curve= 0 ,0
Exp/Cntr=0.3,0.1

Type RM Length L Ch R = 1 ,3247.3  ,263.8,258.4,254.1
XS GIS Cut Line= 3
     2067162.224      373661.593     2067029.943      373627.973
     2066896.634       373598.29
#Sta/Elev= 29
       0 2692.34     9.8 2686.72    19.5 2680.09    29.2  2675.2      39 2673.44
    58.5 2673.53    68.2 2672.36      78 2670.25    87.7 2667.86    97.5 2665.34
   107.2 2663.14     117 2662.15   126.7 2662.81   128.8  2663.3   136.5 2665.15
   143.8 2667.43   146.2 2668.19     156 2670.55   165.8 2672.02   175.5 2673.01
   185.3 2673.62     195 2673.82   204.8  2673.6   224.3 2672.63     234 2672.44
   243.8  2672.8   253.6 2673.78   263.3 2675.28   273.1    2677
#Mann= 3 , 0 , 0
       0      .1       0   128.8    .045       0   143.8      .1       0
Bank Sta=128.8,143.8
XS Rating Curve= 0 ,0
Exp/Cntr=0.3,0.1

Type RM Length L Ch R = 1 ,2989    ,305.5,286.1,277.6
XS GIS Cut Line= 3
     2067216.975      373382.862     2067080.544      373378.531
     2066944.113        373374.2
#Sta/Elev= 26
       0 2682.01     9.8 2678.66    19.5 2675.02    29.2 2670.38      39  2665.9
    48.8 2663.69    58.5 2663.35    68.2 2663.11      78 2662.04    87.8  2660.3
    97.5 2658.16   107.2 2655.75     117 2653.88   126.8 2653.42   130.4 2653.73
   136.5 2654.23   145.4 2655.57     156 2657.25   165.8 2658.58   175.5 2659.71
   185.2 2660.62     195  2661.4   214.5 2662.67   253.5 2664.66   263.2 2665.33
     273 2666.32
#Mann= 3 , 0 , 0
       0      .1       0   130.4    .045       0   145.4      .1       0
Bank Sta=130.4,145.4
XS Rating Curve= 0 ,0
Exp/Cntr=0.3,0.1

Type RM Length L Ch R = 1 ,2702.8  ,359.5,361.7,363.9
XS GIS Cut Line= 3
     2067150.662      373089.105     2067017.069      373118.249
     2066882.389      373140.208
#Sta/Elev= 27
       0  2665.2     9.8 2659.82    19.5 2654.16    29.3 2651.72    39.1 2651.86
    48.8 2652.36    58.6 2651.87    68.4 2650.16    78.1 2647.74    87.9 2645.06
    97.7 2643.06    99.7 2642.95   107.4 2642.56   114.7 2643.36   117.2 2643.64
     127 2645.78   136.7 2648.18   146.5 2650.34   156.2 2652.39   195.2 2660.32
     205 2662.67   214.7  2665.7   224.5 2669.11   234.2 2672.31     244 2675.16
   263.4 2680.38   273.2 2683.14
#Mann= 3 , 0 , 0
       0      .1       0    99.7    .045       0   114.7      .1       0
Bank Sta=99.7,114.7
XS Rating Curve= 0 ,0
Exp/Cntr=0.3,0.1

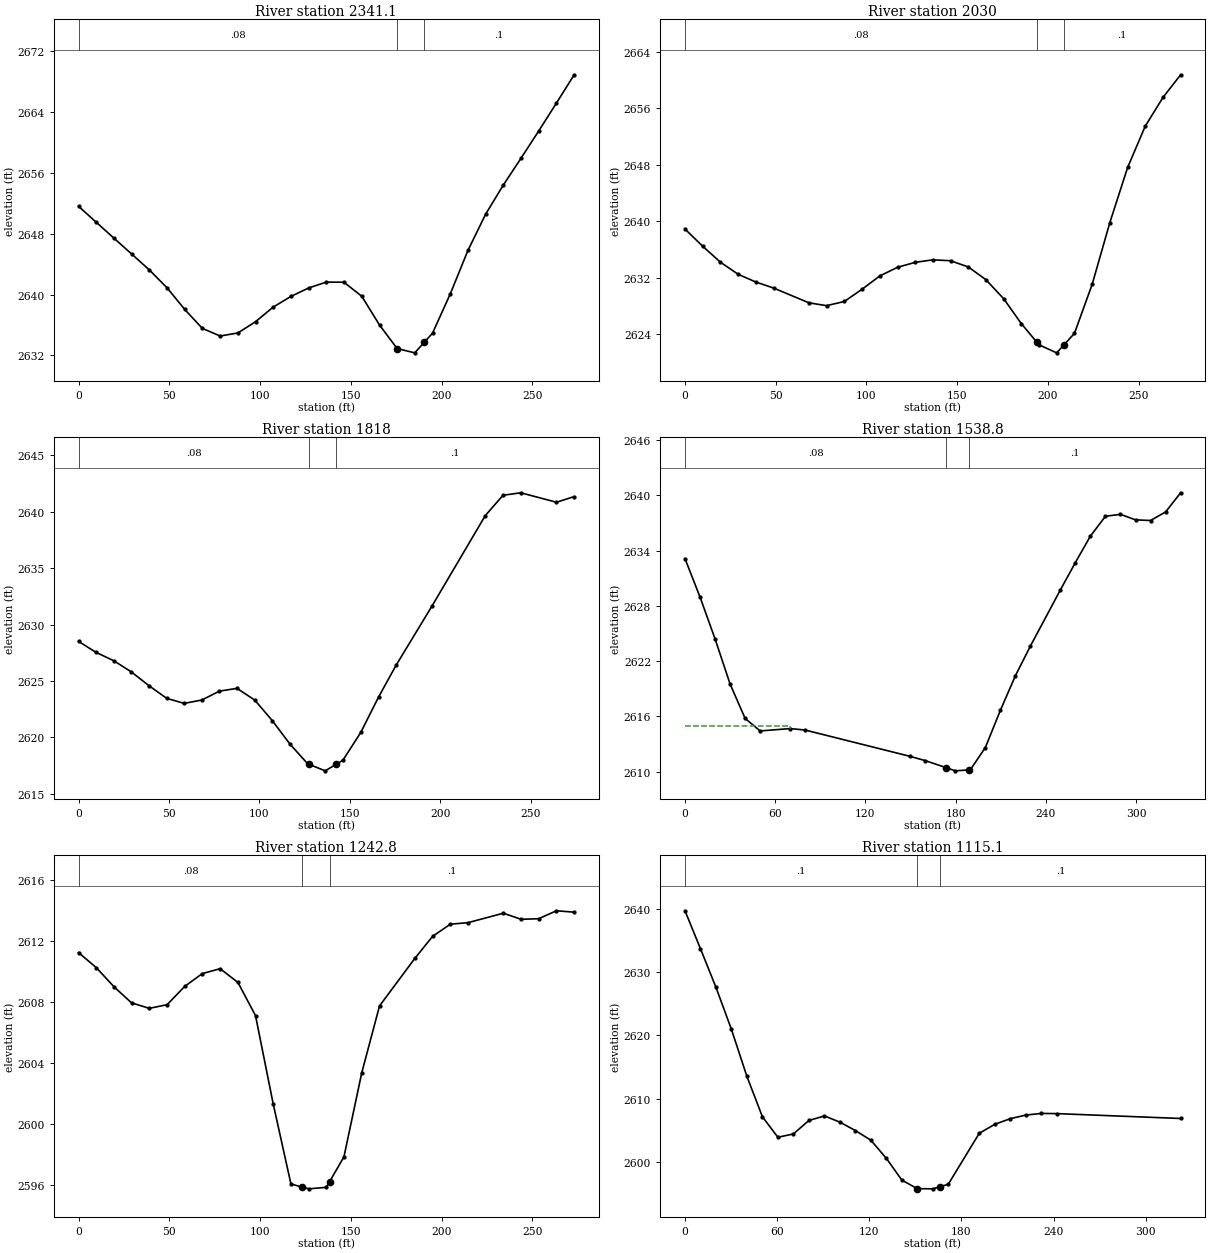
Type RM Length L Ch R = 1 ,2341.1  ,301.1,311.1,321.1
XS GIS Cut Line= 3
      2067147.26      372739.115     2067011.674      372754.881
     2066876.087      372770.647
#Sta/Elev= 30
       0 2651.58     9.8 2649.48    19.5  2647.4    29.2 2645.33      39 2643.23
    48.8 2640.87    58.5 2638.04    68.2 2635.55      78 2634.55    87.8 2634.95
    97.5 2636.43   107.2 2638.34     117 2639.75   126.8 2640.86   136.5 2641.63
   146.2 2641.61     156 2639.77   165.8 2635.99   175.5  2632.9   185.2 2632.34
   190.5 2633.74     195 2634.93   204.8  2640.1   214.5 2645.79   224.2 2650.53
     234 2654.38   243.8 2657.92   253.5 2661.48   263.2 2665.12     273 2668.85
#Mann= 3 , 0 , 0
       0     .08       0   175.5    .045       0   190.5      .1       0
#XS Ineff= 2 , 0
           140.7 2641.52
Permanent Ineff=
       F       F
Bank Sta=175.5,190.5
XS Rating Curve= 0 ,0
Exp/Cntr=0.3,0.1

Type RM Length L Ch R = 1 ,2030    ,214.2,212.1,209
XS GIS Cut Line= 2
     2067187.295      372518.711      2066928.76      372430.592
#Sta/Elev= 30
       0  2638.9     9.8 2636.45    19.5 2634.21    29.3 2632.49      39  2631.4
    48.8 2630.55    68.3 2628.45      78 2628.05    87.8 2628.64    97.6 2630.38
   107.3 2632.25   117.1 2633.48   126.8 2634.18   136.6 2634.54   146.3 2634.41
   156.1 2633.53   165.8 2631.73   175.6 2629.03   185.3 2625.51   193.8  2622.9
   195.1  2622.5   204.8 2621.37   208.8 2622.49   214.6 2624.13   224.4  2631.1
   234.1 2639.82   243.9 2647.62   253.6 2653.46   263.4 2657.54   273.1 2660.74
#Mann= 3 , 0 , 0
       0     .08       0   193.8    .045       0   208.8      .1       0
Bank Sta=193.8,208.8
XS Rating Curve= 0 ,0
Exp/Cntr=0.3,0.1

Type RM Length L Ch R = 1 ,1818    ,274.9,279.1,284.3
XS GIS Cut Line= 3
     2067228.797      372302.491     2067096.817      372268.409
     2066962.482      372238.705
#Sta/Elev= 27
       0 2628.51     9.7 2627.53    19.5 2626.79    29.2  2625.8      39 2624.57
    48.7 2623.46    58.4 2623.01    68.2 2623.31    77.9  2624.1    87.6 2624.34
    97.4  2623.3   107.1 2621.48   116.8 2619.41   126.6 2617.66   127.4 2617.61
   136.3 2617.03   142.4 2617.61   146.1 2617.97     156 2620.44   165.8 2623.57
   175.6 2626.42   195.3 2631.63   224.8 2639.66   234.6 2641.46   244.4 2641.68
   264.1 2640.84   273.9 2641.34
#Mann= 3 , 0 , 0
       0     .08       0   127.4    .045       0   142.4      .1       0
Bank Sta=127.4,142.4
XS Rating Curve= 0 ,0
Exp/Cntr=0.3,0.1

Type RM Length L Ch R = 1 ,1538.8  ,287.5,296.1,304.7
XS GIS Cut Line= 2
     2067284.082      372073.955     2066985.284      371934.694
#Sta/Elev= 27
       0 2633.13      10 2628.96      20 2624.42      30 2619.52      40 2615.78
      50 2614.42    69.9 2614.68    79.9 2614.52   149.8 2611.66   159.8  2611.2
   173.8 2610.43   179.8 2610.09   188.8 2610.19   189.8  2610.2   199.8 2612.62
   209.8 2616.66   219.8 2620.42   229.8 2623.65   249.7 2629.73   259.7 2632.71
   269.7 2635.58   279.7 2637.73   289.7 2637.94   299.7 2637.34   309.7 2637.27
   319.7  2638.2   329.7 2640.28
#Mann= 3 , 0 , 0
       0     .08       0   173.8    .045       0   188.8      .1       0
#XS Ineff= 2 , 0
           70.17 2614.95
Permanent Ineff=
       F       F
Bank Sta=173.8,188.8
XS Rating Curve= 0 ,0
Exp/Cntr=0.3,0.1

Type RM Length L Ch R = 1 ,1242.8  ,126.6,127.7,128.8
XS GIS Cut Line= 3
     2067335.338       371830.38     2067242.325      371730.476
     2067149.311      371630.573
#Sta/Elev= 29
       0 2611.24     9.8 2610.25    19.5    2609    29.2 2607.94      39 2607.58
    48.8 2607.82    58.5 2609.02    68.2 2609.86      78 2610.18    87.8 2609.28
    97.5  2607.1   107.2 2601.33     117 2596.06   123.3 2595.85   126.8 2595.74
   136.5 2595.84   138.3 2596.21   146.2 2597.84     156 2603.35   165.8 2607.74
   185.2 2610.85     195  2612.3   204.8  2613.1   214.5  2613.2     234 2613.82
   243.8 2613.42   253.5 2613.46   263.2 2613.98     273 2613.89
#Mann= 3 , 0 , 0
       0     .08       0   123.3    .045       0   138.3      .1       0
Bank Sta=123.3,138.3
XS Rating Curve= 0 ,0
Exp/Cntr=0.3,0.1

Type RM Length L Ch R = 1 ,1115.1  ,191.1,182.4,173.7
XS GIS Cut Line= 2
     2067440.696      371767.916     2067232.537      371521.321
#Sta/Elev= 26
       0  2639.7    10.1  2633.7    20.2 2627.58    30.2 2620.99    40.3 2613.54
    50.4 2607.15    60.5  2603.9    70.6 2604.43    80.7 2606.56    90.8 2607.27
   100.8  2606.3   110.9 2604.97     121 2603.44   131.1 2600.57   141.2 2597.13
   151.2 2595.78   161.4 2595.75   166.2  2596.1   171.4 2596.47   191.6 2604.53
   201.7 2605.95   211.8 2606.84   221.9 2607.41     232 2607.67     242 2607.64
   322.7 2606.87
#Mann= 3 , 0 , 0
       0      .1       0   151.2    .045       0   166.2      .1       0
Bank Sta=151.2,166.2
XS Rating Curve= 0 ,0
Exp/Cntr=0.3,0.1