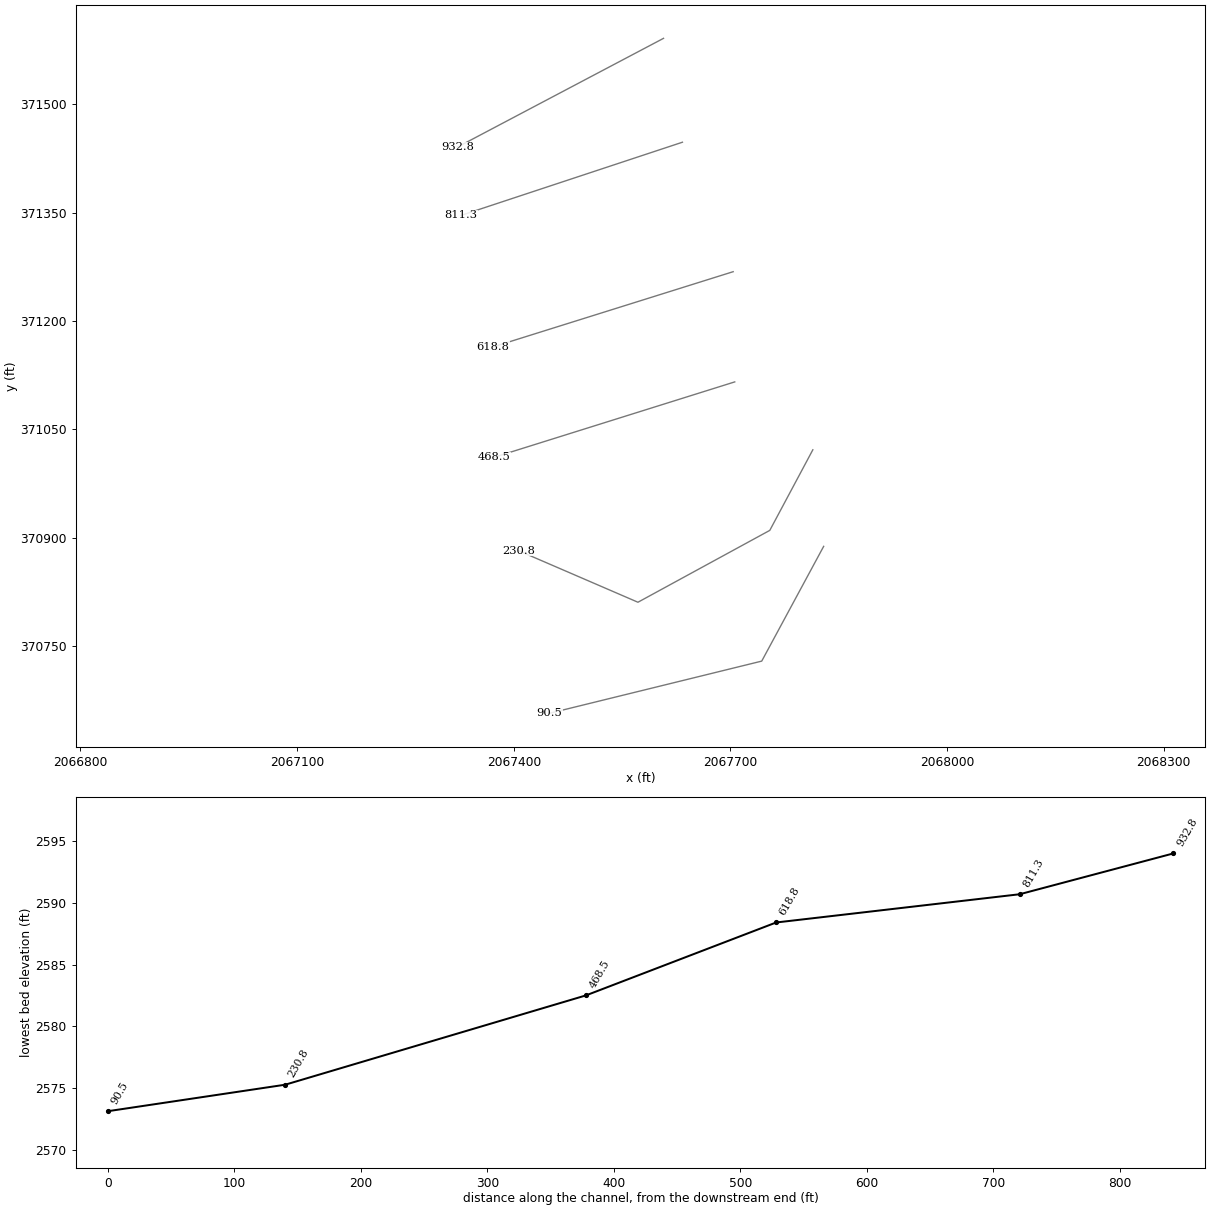
HEC-RAS study BrownCreek.prj: BrownCreek

--- BrownCreek.g01 (geometry) --- (continued)

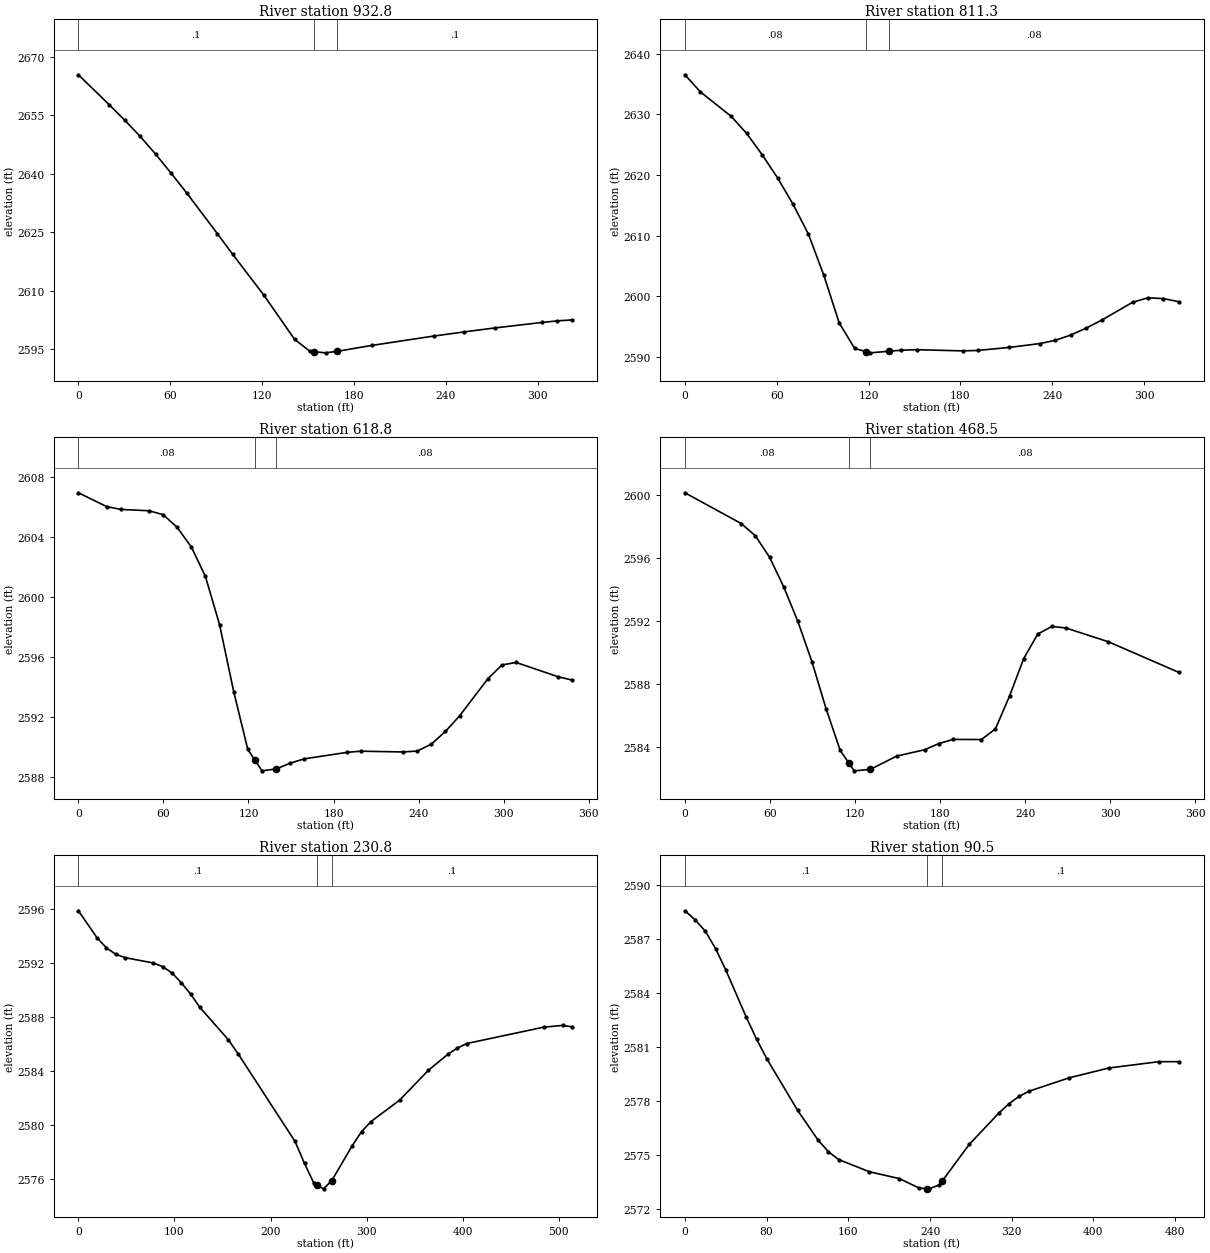
Type RM Length L Ch R = 1 ,932.8   ,125.1,121.5,117.8
XS GIS Cut Line= 2
     2067607.343      371591.235     2067321.929      371440.643
#Sta/Elev= 22
       0 2665.32    20.2  2657.6    30.2 2653.69    40.3 2649.53    50.4 2644.98
    60.5  2640.1    70.6 2635.08    90.8 2624.56   100.8 2619.27     121 2608.88
   141.2 2597.48   151.3 2594.41   153.9 2594.31   161.4 2594.03   168.9 2594.41
   191.6 2595.93     232 2598.33   252.1  2599.4   272.3 2600.43   302.5 2601.81
   312.6 2602.22   322.7 2602.48
#Mann= 3 , 0 , 0
       0      .1       0   153.9    .045       0   168.9      .1       0
Bank Sta=153.9,168.9
XS Rating Curve= 0 ,0
Exp/Cntr=0.3,0.1

Type RM Length L Ch R = 1 ,811.3   ,192.8,192.5,192.2
XS GIS Cut Line= 2
     2067633.522      371447.392     2067327.126      371346.096
#Sta/Elev= 28
       0 2636.51    10.1  2633.7    30.2 2629.67    40.3 2626.86    50.4 2623.37
    60.5 2619.55    70.6 2615.21    80.7 2610.26    90.8 2603.46   100.8 2595.64
   110.9 2591.45   118.2 2590.92     121 2590.72   133.2 2590.98   141.2 2591.15
   151.3 2591.24   181.5 2591.04   191.6 2591.12   211.8 2591.61     232 2592.25
     242 2592.78   252.1 2593.66   262.2  2594.8   272.3 2596.11   292.4 2599.04
   302.5 2599.79   312.6 2599.65   322.7 2599.14
#Mann= 3 , 0 , 0
       0     .08       0   118.2    .045       0   133.2     .08       0
Bank Sta=118.2,133.2
XS Rating Curve= 0 ,0
Exp/Cntr=0.3,0.1

Type RM Length L Ch R = 1 ,618.8   ,150.3,150.3,150.3
XS GIS Cut Line= 2
     2067703.784      371268.121     2067371.097      371163.898
#Sta/Elev= 28
       0 2606.98    19.9 2606.06    29.9 2605.87    49.8 2605.78    59.8 2605.52
    69.7 2604.67    79.7 2603.36    89.6  2601.4    99.6 2598.18   109.6  2593.7
   119.5 2589.86   124.7 2589.12   129.5 2588.43   139.7 2588.56   149.4 2588.94
   159.4 2589.23   189.3 2589.66   199.2 2589.74   229.1 2589.69   239.1 2589.75
     249 2590.21     259 2591.06   268.9 2592.09   288.9 2594.57   298.8 2595.49
   308.8 2595.66   338.7  2594.7   348.6 2594.48
#Mann= 3 , 0 , 0
       0     .08       0   124.7    .045       0   139.7     .08       0
Bank Sta=124.7,139.7
XS Rating Curve= 0 ,0
Exp/Cntr=0.3,0.1

Type RM Length L Ch R = 1 ,468.5   ,233.3,237.7,242.1
XS GIS Cut Line= 2
     2067705.947      371115.509      2067373.26      371011.286
#Sta/Elev= 25
       0 2600.12    39.8 2598.17    49.8 2597.39    59.8 2596.03    69.7 2594.17
    79.7 2591.98    89.6 2589.44    99.6 2586.46   109.6 2583.81   115.8    2583
   119.5 2582.52   130.8 2582.61   149.4 2583.45   169.3 2583.86   179.3 2584.25
   189.3 2584.51   209.2  2584.5   219.1 2585.17   229.1 2587.26   239.1 2589.63
     249 2591.18     259 2591.66   268.9 2591.56   298.8 2590.69   348.6 2588.75
#Mann= 3 , 0 , 0
       0     .08       0   115.8    .045       0   130.8     .08       0
Bank Sta=115.8,130.8
XS Rating Curve= 0 ,0
Exp/Cntr=0.3,0.1

Type RM Length L Ch R = 1 ,230.8   ,146.3,140.3,134.4
XS GIS Cut Line= 4
     2067814.088      371021.513     2067754.472      370909.916
     2067571.902      370810.415     2067406.684      370881.737
#Sta/Elev= 30
       0 2595.85    19.5 2593.84    29.2  2593.1    38.9 2592.63    48.7 2592.38
    77.9 2591.99    87.6 2591.72    97.3 2591.26   107.1 2590.53   116.8 2589.69
   126.5  2588.7   156.2  2586.3   166.1 2585.29   225.5 2578.79   235.4 2577.16
   245.3 2575.68   248.8 2575.54   255.2 2575.28   263.8 2575.89   284.9 2578.45
   294.8 2579.51   304.7 2580.26   334.4 2581.84   364.4 2584.05   384.4 2585.22
   394.4 2585.69   404.4 2586.03   484.4 2587.24   504.4 2587.37   514.4 2587.26
#Mann= 3 , 0 , 0
       0      .1       0   248.8    .045       0   263.8      .1       0
Bank Sta=248.8,263.8
XS Rating Curve= 0 ,0
Exp/Cntr=0.3,0.1

Type RM Length L Ch R = 1 ,90.5    ,89.7,90.5,91.2
XS GIS Cut Line= 3
     2067829.071      370887.802     2067743.306      370728.898
     2067448.952      370656.525
#Sta/Elev= 28
       0 2588.59      10 2588.09    20.1 2587.45    30.1 2586.48    40.1 2585.29
    60.2 2582.66    70.2 2581.45    80.2 2580.36   110.4 2577.49   130.4 2575.84
   140.4  2575.2   150.5 2574.76   180.6 2574.08   209.9  2573.7   229.5 2573.17
   236.9 2573.14   239.2 2573.13     249 2573.35   251.9 2573.56   278.4  2575.6
   307.7 2577.36   317.5 2577.87   327.2 2578.27     337 2578.56   376.1  2579.3
   415.2 2579.85   464.1  2580.2   483.7  2580.2
#Mann= 3 , 0 , 0
       0      .1       0   236.9    .045       0   251.9      .1       0
Bank Sta=236.9,251.9
XS Rating Curve= 0 ,0
Exp/Cntr=0.3,0.1

Chan Stop Cuts=-1
Use User Specified Reach Order=0